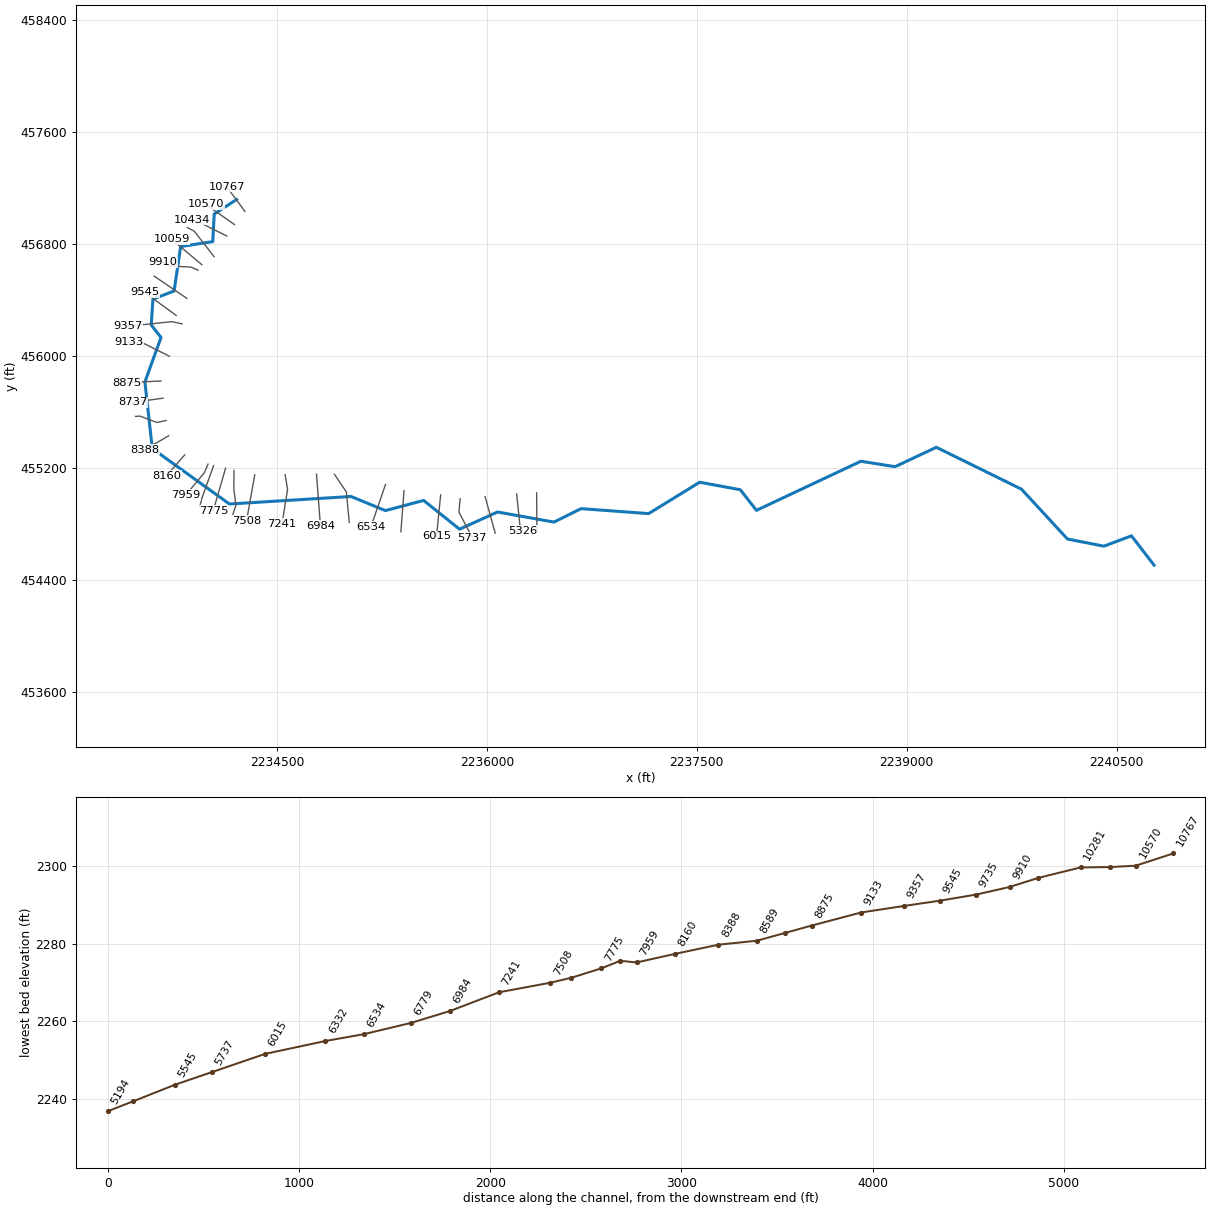
--- BRSHLCKRN.prj (project) ---

Proj Title=BRSHLCKRN
Current Plan=p01
Default Exp/Contr=0,0
English Units
Geom File=g01
Flow File=f01
Plan File=p01
Background Map Layer=Inundation Boundary (01pct Value_0)
BEGIN DESCRIPTION:
----------MODEL BY WOOD PLC 2021----------
Stream Name: Brush Lick Run
Flood Zone: Enhanced Approximate
Pocahontas County, WV
HEC-RAS Version: RAS 6.1
Vertical Datum: NAVD88
Projection: NAD 1983 StatePlane West Virginia S FIPS 4702 (US Feet)
Terrain: 1-meter LIDAR (FEMA Region III 3DEP collected 2016-2018)
Land Use: 2019 NLCD
Hydrologic Method:
WV SIR2010-5033 regression equations
END DESCRIPTION:
DSS File=dss
DSS Export Rating Curves= 0
DSS Export Rating Curve Sorted= 0
DSS Export Volume Flow Curves= 0
DXF OffsetX= 0
DXF OffsetY= 0
DXF ScaleX= 0
DXF ScaleY= 0

--- BRSHLCKRN.p01 (plan) ---

Plan Title=Floodplain
Program Version=6.10
Short Identifier=Floodplain
Geom File=g01
Flow File=f01
Subcritical Flow
K Sum by GR= 0
Std Step Tol= 0.01
Critical Tol= 0.01
Num of Std Step Trials= 20
Max Error Tol= 0.3
Flow Tol Ratio= 0.001
Split Flow NTrial= 30
Split Flow Tol= 0.02
Split Flow Ratio= 0.02
Log Output Level= 0
Friction Slope Method= 1
Unsteady Friction Slope Method= 2
Unsteady Bridges Friction Slope Method= 1
Parabolic Critical Depth
Global Vel Dist= 0 , 0 , 0
Global Log Level= 0
CheckData=True
Encroach Param=-1 ,0,0, 0
Computation Interval=0.1SEC
Output Interval=1SEC
Instantaneous Interval=Max Profile
Mapping Interval=1HOUR
Computation Time Step Use Courant=        0
Computation Time Step Use Time Series=    0
Computation Time Step Count To Double=0
Computation Time Step Max Doubling=0
Computation Time Step Max Halving=0
Computation Time Step Residence Courant=0
Run HTab= 0
Run UNet= 0
Run Sediment= 0
Run PostProcess= 0
Run WQNet= 0
Run RASMapper=-1
UNET Theta= 0
UNET Theta Warmup= 0
UNET ZTol= 0
UNET ZSATol= 0
UNET MxIter= 0
UNET Max Iter WO Improvement= 0
UNET MaxInSteps= 0
UNET DtIC= 0
UNET DtMin= 0
UNET MaxCRTS= 0
UNET WFStab= 0
UNET SFStab= 0
UNET WFX= 1
UNET SFX= 1
UNET Gravity=32.174
UNET 1D Methodology=Finite Difference
UNET DSS MLevel= 1
UNET Pardiso=0
UNET DZMax Abort= 0
UNET Use Existing IB Tables= 0
UNET Froude Reduction=False
UNET Froude Limit= 0
UNET Froude Power= 0
UNET D1 Cores= 0
UNET WindReference=Eulerian
UNET WindDragFormulation=Hsu (1988)
UNET D2 Coriolis=0
UNET D2 Cores= 0
UNET D2 Theta= 1
UNET D2 Theta Warmup= 1
UNET D2 Z Tol= 0.01
UNET D2 Volume Tol= 0.01
UNET D2 Max Iterations= 20
UNET D2 Equation= 0
UNET D2 RampUpFraction=0.1
UNET D2 TimeSlices= 1
UNET D2 Turbulence Formulation=Non-Conservative (original)
UNET D2 Eddy Viscosity=0.3
UNET D2 Transverse Eddy Viscosity=0.1
UNET D2 Smagorinsky Mixing=0
UNET D2 BCVolumeCheck=0
UNET D2 Cores=0
UNET D2 SolverType=PARDISO (Direct)
UNET D2 Minimum Iterations= 2147483647
UNET D2 Maximum Iterations= 2147483647
UNET D2 Restart Number= 10
UNET D2 Relaxation Coeff=1.3
UNET D2 SOR Precondition Iterations= 10
UNET D2 ILUT Maximum Fill= 8
UNET D2 ILUT Tolerance=1E-08
UNET D1D2 MaxIter= 0
UNET D1D2 ZTol=0.01
UNET D1D2 QTol=0.1
UNET D1D2 MinQTol=1
DSS File=dss
Write IC File= 0
Write IC File at Fixed DateTime=0
Write IC File at Sim End=0
Echo Input=False
Echo Parameters=False
Echo Output=False
Write Detailed= 0
HDF Write Warmup=0
HDF Write Time Slices=0
HDF Flush=0
HDF Compression= 1
HDF Chunk Size= 1
HDF Spatial Parts= 1
HDF Use Max Rows=0
HDF Fixed Rows= 1
Calibration Method= 0
Calibration Iterations= 20
Calibration Max Change=0.05
Calibration Tolerance=0.2
Calibration Maximum=1.5
Calibration Minimum=0.5
Calibration Optimization Method= 1
WQ AD Non Conservative
WQ ULTIMATE=-1
WQ Max Comp Step=1HOUR
WQ Output Interval=15MIN
WQ Output Selected Increments= 0
WQ Output face flow=0
WQ Output face velocity=0
WQ Output face area=0
WQ Output face dispersion=0
WQ Output cell volume=0
WQ Output cell surface area=0
WQ Output cell continuity=0
WQ Output cumulative cell continuity=0
WQ Output face conc=0
WQ Output face dconc_dx=0
WQ Output face courant=0
WQ Output face peclet=0
WQ Output face adv mass=0
WQ Output face disp mass=0
WQ Output cell mass=0
WQ Output cell source sink temp=0
WQ Output nsm pathways=0
WQ Output nsm derived pathways=0
WQ Create Restart=0
WQ Fixed Restart=0
WQ System Summary=0
WQ Write To DSS=0
Sorting and Armoring Iterations= 10
XS Update Threshold= 0.02
Bed Roughness Predictor= 0
Hydraulics Update Threshold= 0.02
Energy Slope Method= 1
Volume Change Method= 1
Sediment Retention Method= 0
Sediment TS Multiplier= 1
Warm Up Method= 0
XS Weighting Method= 0
Number of US Weighted Cross Sections= 1
Number of DS Weighted Cross Sections= 1
Upstream XS Weight=0
Main XS Weight=1
Downstream XS Weight=0
Number of DS XS's Weighted with US Boundary= 1
Upstream Boundary Weight= 1
Weight of XSs Associated with US Boundary= 0
Number of US XS's Weighted with DS Boundary= 1
Downstream Boundary Weight= 0.5
Weight of XSs Associated with DS Boundary= 0.5
Percentile Method= 0
Sediment Output Level= 3
Mass or Volume Output= 0
Output Increment Type= 1
Profile and TS Output Increment= 1
Transport Output Increment 1
XS Output Flag= 0
XS Output Increment= 10
Read HDF5 Sediment Hotstart= 0
Sediment Hotstart Type= 0
Write Gradation File= 0
Read Gradation Hotstart= 0
Write HDF5 File= 1
Write Binary Output= 1
Write DSS Sediment File= 0
DSS Sediment Output Type= 1
SV Curve= 0
Specific Gage Flag= 0
Subcell Erosion Methods= 0
Subcell Deposition Methods= 0
Advection Scheme= 1
Matrix Solver= 0
Implicit Weighting Factor= 1
Maximum Outer Loop Convergence Iterations= 5
Convergence Maximum Absolute= 0.001
Convergence RMSE= 0.0001
Grain Fractions Max Abs Error= 0.001
Max Subgrid Regions= 1
Max Subgrid Length Scale= 3.402823E+38
Initial Layer Thickness= 3.402823E+38
Min Layer Thickness= 3.402823E+38
Max Layer Thickness= 3.402823E+38
Number of Layers= 5

--- BRSHLCKRN.f01 (steady flow) ---

Flow Title=Flow
Program Version=6.10
Number of Profiles= 6
Profile Names=01pct,10pct,04pct,02pct,0_2pct,01plus
River Rch & RM=BRSHLCKRN,Main,10767
     602     318     423     509     839     890
River Rch & RM=BRSHLCKRN,Main,6015
     675     359     476     572     940     998
River Rch & RM=BRSHLCKRN,Main,3843
    1020     552     727     870    1410    1510
Boundary for River Rch & Prof#=BRSHLCKRN,Main            , 1
Up Type= 0
Dn Type= 3
Dn Slope=0.02022
Boundary for River Rch & Prof#=BRSHLCKRN,Main            , 2
Up Type= 0
Dn Type= 3
Dn Slope=0.02022
Boundary for River Rch & Prof#=BRSHLCKRN,Main            , 3
Up Type= 0
Dn Type= 3
Dn Slope=0.02022
Boundary for River Rch & Prof#=BRSHLCKRN,Main            , 4
Up Type= 0
Dn Type= 3
Dn Slope=0.02022
Boundary for River Rch & Prof#=BRSHLCKRN,Main            , 5
Up Type= 0
Dn Type= 3
Dn Slope=0.02022
Boundary for River Rch & Prof#=BRSHLCKRN,Main            , 6
Up Type= 0
Dn Type= 3
Dn Slope=0.02022
DSS Import GetInterval= 0
DSS Import GetPeak= 0
DSS Import FillOption= 0

--- BRSHLCKRN.g01 (geometry) ---

Geom Title=Geometry
Program Version=6.10

River Reach=BRSHLCKRN       ,Main
Reach XY= 30
     2234212.969       457117.83     2234052.473      457014.106
     2234042.102      456816.469     2233812.852      456781.468
      2233766.12      456463.667     2233614.598      456405.667
     2233602.616      456220.176      2233672.55      456131.305
     2233557.368      455813.415     2233610.163      455337.137
     2234161.185      454940.543     2235029.987      454994.347
     2235275.489      454893.386     2235548.695      454966.183
     2235805.356      454760.423     2236076.451      454883.481
     2236479.736      454811.236     2236673.358      454907.396
      2237156.08      454871.976     2237520.678      455096.244
     2237811.367      455042.515     2237926.407      454895.147
2238672.28165439455246.114470693 2238916.9275437455207.450597988
     2239211.622      455346.026     2239819.823      455046.677
     2240148.315      454690.367     2240408.556      454639.082
     2240605.648      454712.853      2240767.13      454503.369

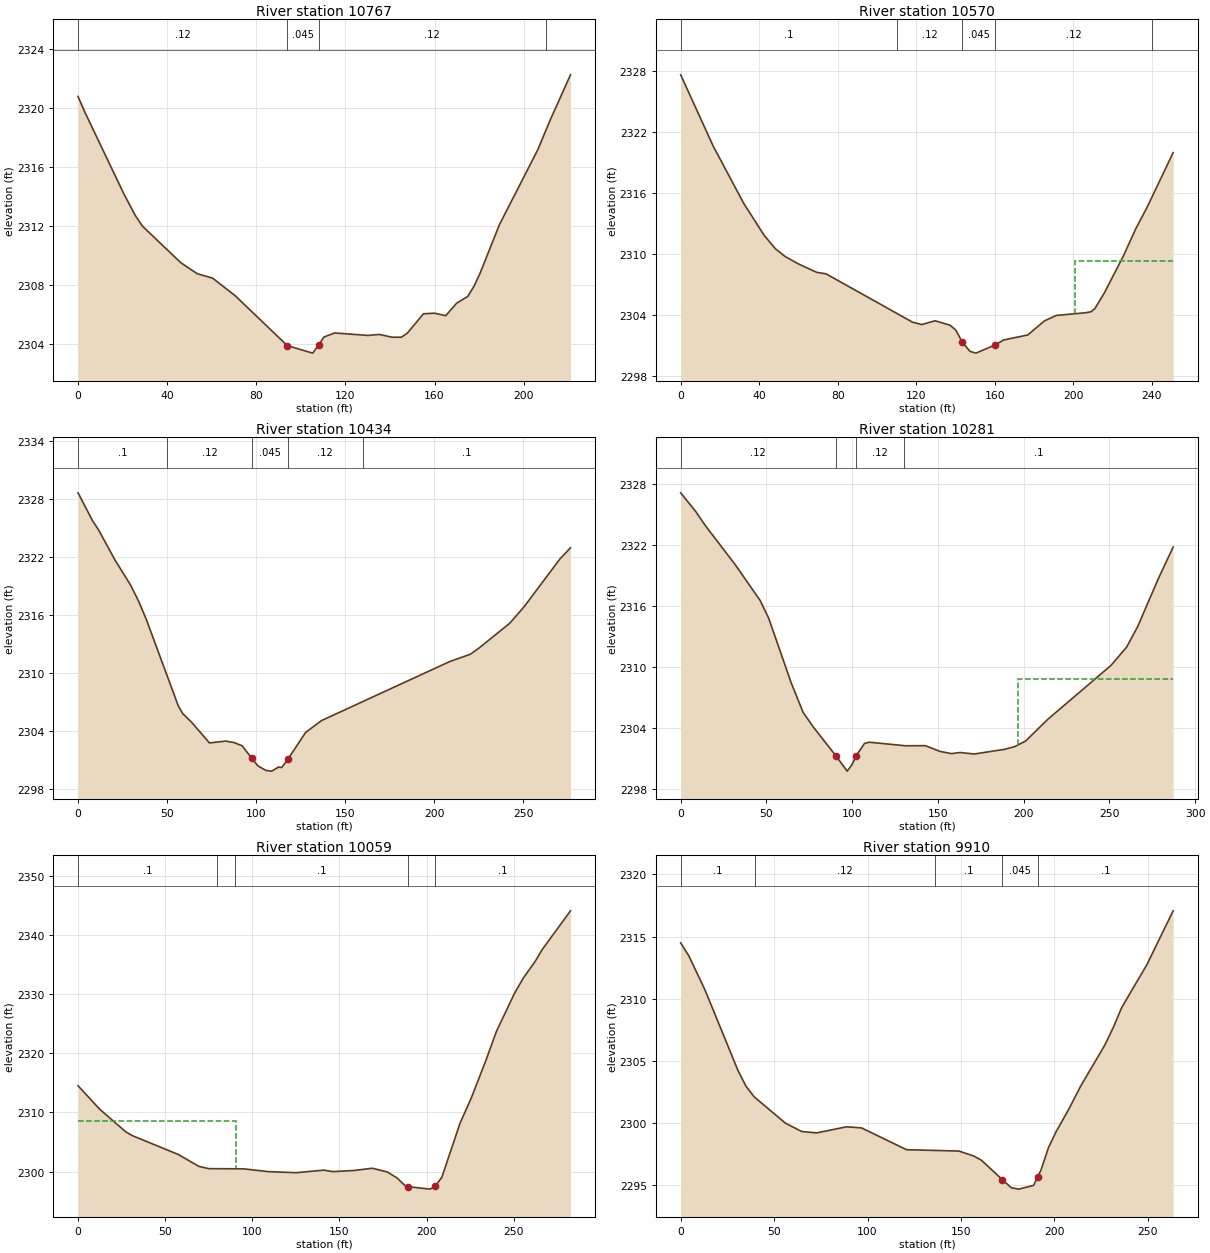
Type RM Length L Ch R = 1 ,10767   ,190.6,196.8,200.1
XS GIS Cut Line= 2
2234271.98614926457032.5063083382234140.63888265457210.269526313
#Sta/Elev= 30
       0  2320.8     3.2 2319.69    20.7 2314.15    25.7 2312.72    28.9    2312
    46.1 2309.52    53.5 2308.77    60.4 2308.47    70.5 2307.28    93.9 2303.89
   105.3 2303.38  107.98 2303.93   110.3 2304.47   115.2 2304.75   130.1 2304.58
   135.1 2304.65     141 2304.46   145.1 2304.46   147.8 2304.74     155 2306.05
     160 2306.09     165 2305.92   169.9 2306.77   174.9 2307.23   177.7 2307.92
   180.5 2308.83   189.1  2312.1   206.3 2317.18     212 2319.24     221 2322.27
#Mann= 4 ,-1,0
       0     .12       0    93.9    .045       0  107.98     .12       0
     210      .1       0
Bank Sta=93.9,107.98
XS Rating Curve= 0 ,0
Exp/Cntr(USF)=0,0
Exp/Cntr=0.3,0.1

Type RM Length L Ch R = 1 ,10570   ,134,135.8,134.3
XS GIS Cut Line= 2
2234196.93056834456938.6868321842233991.51529423457082.872553431
#Sta/Elev= 30
       0 2327.66    16.7 2320.58    32.2 2314.96    42.5 2311.84    48.3  2310.5
    53.1 2309.76    59.6 2309.05    69.3 2308.18    74.1 2308.03   118.2 2303.26
   122.9 2303.03   129.7  2303.4   137.3 2302.96   140.2 2302.49   143.6 2301.26
   147.5 2300.38   150.5 2300.21   160.3 2301.02   164.5  2301.5   176.9    2302
   185.4 2303.39   191.5 2303.93   206.2 2304.19   209.1 2304.29   211.1  2304.6
     216 2306.17   225.7 2309.82     232  2312.5   237.8 2314.63     251 2319.99
#Mann= 5 ,-1,0
       0      .1       0     110     .12       0   143.6    .045       0
   160.3     .12       0     240      .1       0
#XS Ineff= 2 , 0
                           201.1         2309.31
Permanent Ineff=
       F       F
Bank Sta=143.6,160.3
XS Rating Curve= 0 ,0
Exp/Cntr(USF)=0,0
Exp/Cntr=0.3,0.1

Type RM Length L Ch R = 1 ,10434   ,157.3,153.4,148.1
XS GIS Cut Line= 3
2234142.61402951456856.7182372282233953.98750377456950.537713382
2233891.77037748456972.264328912
#Sta/Elev= 30
       0 2328.67     8.1  2325.8    11.7 2324.78    20.6 2321.76    29.5 2319.12
      34 2317.46    38.5 2315.49    56.3 2306.61    58.8 2305.81    63.9 2304.89
    73.8 2302.77    83.1 2302.96    87.6 2302.81    92.1 2302.48    97.6 2301.19
     101  2300.4   105.5 2299.92   108.8 2299.85   112.6 2300.27   114.4 2300.22
   117.8 2301.06   127.8 2303.85   136.7 2305.08   208.8  2311.2   220.4 2311.96
   225.3 2312.61   242.4 2315.15   250.7 2316.91   270.7 2321.83   276.6 2322.98
#Mann= 5 ,-1,0
       0      .1       0      50     .12       0    97.6    .045       0
   117.8     .12       0     160      .1       0
Bank Sta=97.6,117.8
XS Rating Curve= 0 ,0
Exp/Cntr(USF)=0,0
Exp/Cntr=0.3,0.1

Type RM Length L Ch R = 1 ,10281   ,213.7,221.7,222.8
XS GIS Cut Line= 3
2234051.75727366456708.5822222492233909.54669928 456891.28330739
2233860.16802762456916.960216653
#Sta/Elev= 30
       0 2327.09     8.7 2325.27    14.4 2323.87    31.9 2320.01    46.4  2316.5
    51.4 2314.74    64.4 2308.45    71.4 2305.52    77.5 2304.05    90.5 2301.26
    97.1 2299.75    99.9 2300.38   102.1  2301.2   107.2 2302.47     110 2302.59
   131.2 2302.24   142.7 2302.25   151.2 2301.69   157.9 2301.47     163 2301.58
   171.1 2301.43   188.8 2301.89   194.7 2302.15   201.2 2302.71   213.9 2304.81
   251.1 2310.16   260.1 2311.94   266.6 2313.98   278.4  2318.6   287.2 2321.76
#Mann= 4 ,-1,0
       0     .12       0    90.5    .045       0   102.1     .12       0
     130      .1       0
#XS Ineff= 2 , 0
                          196.91         2308.78
Permanent Ineff=
       F       F
Bank Sta=90.5,102.1
XS Rating Curve= 0 ,0
Exp/Cntr(USF)=0,0
Exp/Cntr=0.3,0.1

Type RM Length L Ch R = 1 ,10059   ,140,149.4,157.6
XS GIS Cut Line= 2
2233964.27029443456651.5215249782233747.57656606456832.925126027
#Sta/Elev= 30
       0 2314.51    12.6  2310.5    27.5  2306.7    31.4 2306.05    57.5  2302.9
    69.4 2300.88    75.1  2300.5    94.9 2300.47   109.1    2300   125.3 2299.82
     141 2300.25   146.2    2300   158.4 2300.19   168.8 2300.57   177.5 2299.94
     183 2298.94   187.9 2297.57   189.5 2297.45     202 2297.04  204.89 2297.49
   208.8 2299.06   219.2 2308.18   225.6  2312.4   234.1 2318.84   240.1  2323.7
   250.5 2330.16   255.7  2332.8   262.5 2335.61   266.2 2337.47   282.6 2344.08
#Mann= 5 ,-1,0
       0      .1       0      80     .12       0      90      .1       0
   189.5    .045       0  204.89      .1       0
#XS Ineff= 2 , 0
            90.7 2308.59
Permanent Ineff=
       F       F
Bank Sta=189.5,204.89
XS Rating Curve= 0 ,0
Exp/Cntr(USF)=0,0
Exp/Cntr=0.3,0.1

Type RM Length L Ch R = 1 ,9910    ,183.2,174.3,166.3
XS GIS Cut Line= 4
2233936.18693615456612.348297337 2233884.9695675 456634.97922767
2233733.69966475456642.125837248 2233683.6733977456667.734521572
#Sta/Elev= 30
       0 2314.49     4.4 2313.44    13.1 2310.68    30.6 2304.26      35 2302.96
    39.4 2302.11      56 2300.01    64.8 2299.33    72.8 2299.22    88.8 2299.71
    96.8 2299.62   120.9 2297.87   148.9 2297.76   156.9 2297.36   160.9 2297.03
   172.2 2295.46   176.9 2294.82   180.9  2294.7   188.9    2295     1912295.656
   192.9 2296.25   196.9 2298.05     201 2299.33   207.9 2301.17   214.1 2302.98
   227.1  2306.3   231.7 2307.74   236.1 2309.31   249.5 2312.73   263.6 2317.07
#Mann= 5 ,-1,0
       0      .1       0      40     .12       0  135.99      .1       0
   172.2    .045       0     191      .1       0
Bank Sta=172.2,191
XS Rating Curve= 0 ,0
Exp/Cntr(USF)=0,0
Exp/Cntr=0.3,0.1

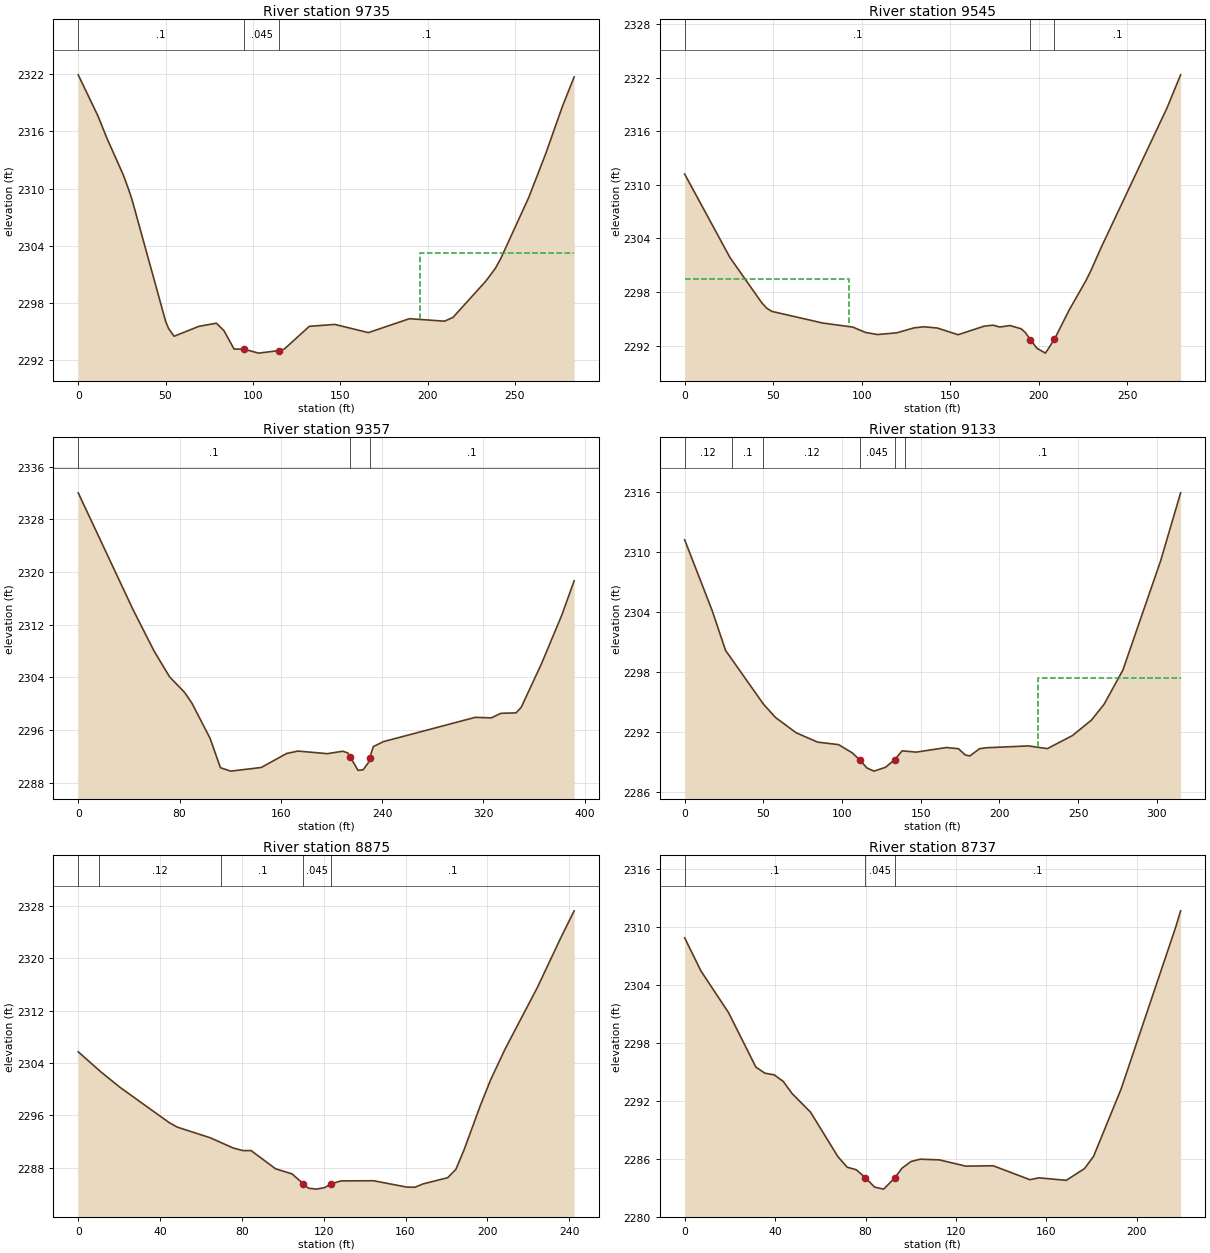
Type RM Length L Ch R = 1 ,9735    ,187.8,190,186
XS GIS Cut Line= 2
2233857.63141673456410.6918560672233622.71971298456570.167125369
#Sta/Elev= 30
       0 2321.92    11.4 2317.57    16.3 2315.33    25.9 2311.39    28.8 2309.93
    30.8 2308.84    50.1 2296.04    51.8  2295.3    54.9 2294.51    69.1 2295.55
    79.1 2295.88    83.5 2295.08    89.2 2293.17      95 2293.15   103.3 2292.74
   115.1 2293.01     118 2293.17   132.3 2295.55   146.9 2295.75   166.1 2294.89
   189.6 2296.35   209.7 2296.09   214.5 2296.48   233.2 2300.26   238.7  2301.6
   241.9 2302.66     258  2309.1   267.7 2313.69   277.3 2318.67   283.9  2321.7
#Mann= 3 ,-1,0
       0      .1       0      95    .045       0   115.1      .1       0
#XS Ineff= 2 , 0
                          195.42         2303.22
Permanent Ineff=
       F       F
Bank Sta=95,115.1
XS Rating Curve= 0 ,0
Exp/Cntr(USF)=0,0
Exp/Cntr=0.3,0.1

Type RM Length L Ch R = 1 ,9545    ,178.2,188.6,196.2
XS GIS Cut Line= 2
2233780.87153607456288.9348039862233554.56223274 456454.36558127
#Sta/Elev= 30
       0  2311.2    25.6 2301.86    43.6 2296.79    46.5 2296.17    49.3 2295.83
      78 2294.53    95.1 2294.07   102.1 2293.48   108.9 2293.24   119.8 2293.43
   129.7 2293.99   135.2 2294.11   142.8 2293.97   154.5 2293.22   169.3 2294.18
   174.3 2294.29   178.1 2294.08   183.9 2294.25   190.2 2293.88   192.5 2293.48
   195.3 2292.68   199.1  2291.7   203.9 2291.16     209 2292.72   217.3 2295.98
   226.8 2299.28   229.7 2300.44   235.4 2302.99   272.6  2318.6   280.3 2322.31
#Mann= 3 ,-1,0
       0      .1       0   195.3    .045       0     209      .1       0
#XS Ineff= 2 , 0
           92.63 2299.43
Permanent Ineff=
       F       F
Bank Sta=195.3,209
XS Rating Curve= 0 ,0
Exp/Cntr(USF)=0,0
Exp/Cntr=0.3,0.1

Type RM Length L Ch R = 1 ,9357    ,233.3,223.9,215.8
XS GIS Cut Line= 3
2233822.64023716456228.6215337142233748.57222967456244.422708645
2233434.52387791456210.845211917
#Sta/Elev= 30
       0 2332.01    43.4 2314.25    59.9 2308.01    72.1 2304.11    84.2 2301.69
    89.9 2300.06   104.1 2294.78   112.3 2290.31   120.4 2289.79   144.5 2290.34
   164.6 2292.47   173.5 2292.83   196.8 2292.44   208.9 2292.81   212.9 2292.54
   214.62291.976     221 2289.91     225 2289.99     229 2291.05   230.2 2291.79
     233 2293.51   241.1 2294.27   313.5 2297.95   326.2 2297.87   333.8 2298.56
   345.7 2298.63   349.7 2299.43   365.8 2306.08   381.9 2313.48   391.6 2318.67
#Mann= 3 ,-1,0
       0      .1       0   214.6    .045       0   230.2      .1       0
Bank Sta=214.6,230.2
XS Rating Curve= 0 ,0
Exp/Cntr(USF)=0,0
Exp/Cntr=0.3,0.1

Type RM Length L Ch R = 1 ,9133    ,249,257.7,263.4
XS GIS Cut Line= 3
 2233731.7834813455997.529350346 2233538.2190884456094.311546799
2233439.46174508456097.274267099
#Sta/Elev= 30
       0 2311.23    17.5 2304.14      26 2300.17    50.1 2294.79    57.7 2293.47
    70.8 2291.94    84.5    2291    97.8 2290.75   106.5 2289.93   111.4  2289.2
   115.8 2288.42   120.3  2288.1   127.6 2288.48   133.6 2289.26   138.2 2290.13
   147.1    2290   166.4 2290.46     174 2290.34   178.4 2289.71   181.3 2289.62
   187.4 2290.34   191.9 2290.44   218.5 2290.62   230.5 2290.35   246.5 2291.66
   258.5  2293.2   266.5 2294.77   278.5  2298.2   302.5 2309.13   315.2 2315.93
#Mann= 6 ,-1,0
       0     .12       0      30      .1       0      50     .12       0
   111.4    .045       0   133.6     .12       0     140      .1       0
#XS Ineff= 2 , 0
                          224.42         2297.46
Permanent Ineff=
       F       F
Bank Sta=111.4,133.6
XS Rating Curve= 0 ,0
Exp/Cntr(USF)=0,0
Exp/Cntr=0.3,0.1

Type RM Length L Ch R = 1 ,8875    ,137.8,138.4,139.9
XS GIS Cut Line= 2
2233672.52907531455820.3865460922233430.41012399455807.994399117
#Sta/Elev= 30
       0 2305.72      11 2302.67    20.4 2300.29    44.4 2294.91    48.4 2294.21
    64.5 2292.58    75.8 2291.01    80.5 2290.62    84.5 2290.62    96.5 2287.83
   104.5 2287.06   110.1 2285.52   112.5 2284.87   116.5 2284.73   120.5 2284.97
   123.6 2285.53   128.5 2285.99   144.4 2286.01   160.6 2285.04   164.6 2285.02
   168.6 2285.53   180.6 2286.48   184.6 2287.76   188.6 2290.74   196.6 2297.55
   201.5 2301.38   208.6 2306.11   224.4 2315.53   235.8 2323.09   242.4 2327.26
#Mann= 5 ,-1,0
       0      .1       0      10     .12       0      70      .1       0
   110.1    .045       0   123.6      .1       0
Bank Sta=110.1,123.6
XS Rating Curve= 0 ,0
Exp/Cntr(USF)=0,0
Exp/Cntr=0.3,0.1

Type RM Length L Ch R = 1 ,8737    ,153.3,148.2,140.6
XS GIS Cut Line= 2
2233687.34267681455697.3070266542233470.07652151455666.692250225
#Sta/Elev= 30
       0 2308.87     7.2 2305.44    19.4 2301.13    31.5 2295.48    35.5 2294.85
    39.6 2294.68    43.6    2294    47.6 2292.72    55.7 2290.81    67.8  2286.2
    71.9 2285.11    75.9 2284.85    79.9 2284.04      84 2283.05      88 2282.84
    92.9 2283.99    96.1    2285   100.1  2285.7   104.2 2285.94   112.7 2285.87
   124.4 2285.22   136.5 2285.26   152.7 2283.82   156.7 2284.01   168.8 2283.75
   176.9 2284.97   180.9 2286.24   193.1 2293.23   217.3 2310.03   219.4 2311.67
#Mann= 3 ,-1,0
       0      .1       0    79.9    .045       0    92.9      .1       0
Bank Sta=79.9,92.9
XS Rating Curve= 0 ,0
Exp/Cntr(USF)=0,0
Exp/Cntr=0.3,0.1

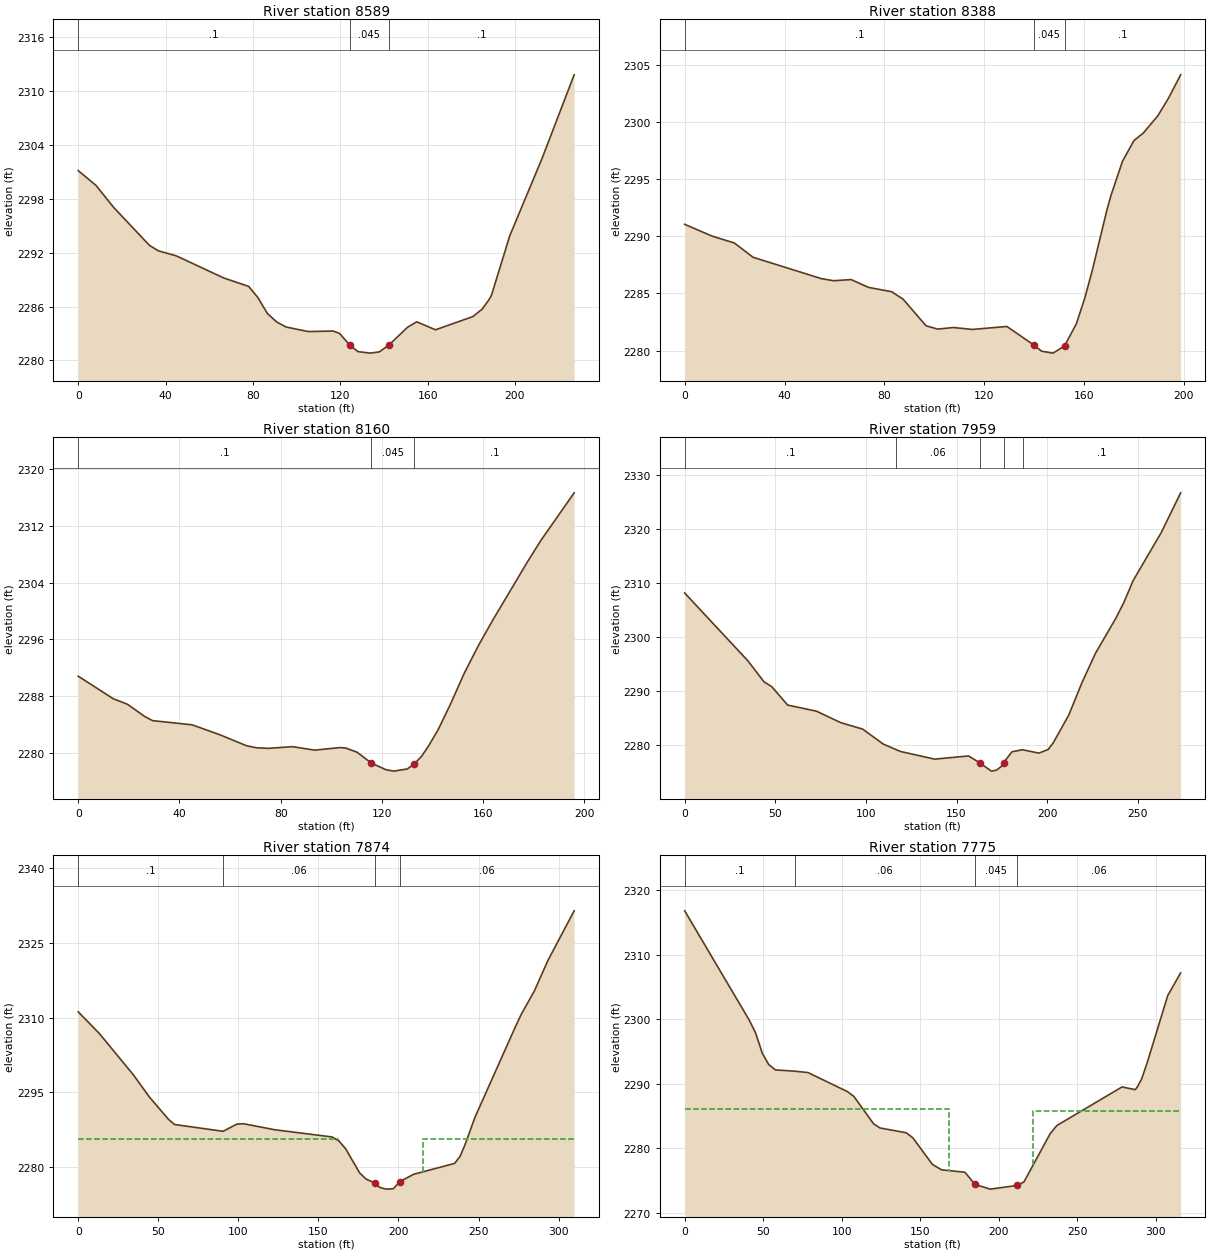
Type RM Length L Ch R = 1 ,8589    ,190.6,201.1,212.9
XS GIS Cut Line= 4
2233708.08171891455537.3201304762233642.90187232455523.494102411
2233522.41791346455568.922480338 2233490.8155636455566.947333472
#Sta/Elev= 30
       0 2301.15     8.1 2299.51    16.3 2297.03    32.6 2292.82    36.7 2292.21
    44.9 2291.65    66.6 2289.19    78.1 2288.24    82.4 2286.96    86.6 2285.24
    90.9 2284.28    95.2 2283.72   105.4 2283.21   116.8 2283.27   119.7    2283
  124.34 2281.71   128.1 2280.98   133.7 2280.81   137.9 2280.95   142.2  2281.7
   150.8 2283.69     155  2284.3   163.6 2283.41   180.7 2284.88     185 2285.72
     188 2286.73   189.2 2287.22   197.6 2293.88   212.4  2302.5   227.1 2311.82
#Mann= 3 ,-1,0
       0      .1       0  124.34    .045       0   142.2      .1       0
Bank Sta=124.34,142.2
XS Rating Curve= 0 ,0
Exp/Cntr(USF)=0,0
Exp/Cntr=0.3,0.1

Type RM Length L Ch R = 1 ,8388    ,222.7,227.2,230.2
XS GIS Cut Line= 2
2233727.83318757455428.6870528242233555.99541019455328.942136071
#Sta/Elev= 30
       0 2291.04    11.1    2290    19.9 2289.41    27.4 2288.16    54.8 2286.29
    59.7 2286.11    66.7 2286.21    73.6 2285.53    82.9 2285.15    87.5  2284.5
    96.7 2282.17   101.4 2281.88   107.7 2282.02   115.2 2281.85   129.1 2282.11
   139.9 2280.49     143 2279.95   147.6 2279.78   152.2 2280.41   156.9 2282.33
   160.3 2284.59   163.3    2287   169.1 2292.23   170.7  2293.5   175.4 2296.55
     180 2298.36   183.8 2299.03   189.6 2300.54   193.9 2302.09   198.7 2304.11
#Mann= 3 ,-1,0
       0      .1       0   139.9    .045       0   152.2      .1       0
Bank Sta=139.9,152.2
XS Rating Curve= 0 ,0
Exp/Cntr(USF)=0,0
Exp/Cntr=0.3,0.1

Type RM Length L Ch R = 1 ,8160    ,199.8,200.9,200.4
XS GIS Cut Line= 2
2233841.40413239455291.4143456092233713.01958607455143.278330629
#Sta/Elev= 30
       0  2290.8    13.8 2287.63    19.5 2286.83    26.3 2285.11    29.4 2284.53
      45 2283.94    55.9 2282.55    66.5 2280.99    70.5  2280.7    75.2 2280.62
    84.7 2280.86    93.5 2280.37   103.5 2280.73   105.7 2280.67   110.2 2280.08
   115.9 2278.54   121.6 2277.61   124.7 2277.41   130.1 2277.72   132.9 2278.46
   135.7  2279.5   138.6 2281.04   142.3 2283.29   147.1 2286.84   152.7 2291.31
   158.4 2295.27   164.1 2298.86   177.6 2306.95   182.9 2309.96     196 2316.65
#Mann= 3 ,-1,0
       0      .1       0   115.9    .045       0   132.9      .1       0
Bank Sta=115.9,132.9
XS Rating Curve= 0 ,0
Exp/Cntr(USF)=0,0
Exp/Cntr=0.3,0.1

Type RM Length L Ch R = 1 ,7959    ,81.1,85.4,90.5
XS GIS Cut Line= 3
 2234008.3040426455225.246925585 2233981.6395599455164.017372727
2233849.30471985455005.018049982
#Sta/Elev= 30
       0 2308.14      35 2295.55    43.7 2291.73    48.1  2290.8    56.8 2287.41
    72.7 2286.28    86.1 2284.16    98.2 2282.96   109.6 2280.18   119.1 2278.82
   137.9 2277.41   156.6    2278   162.9  2276.7   169.2 2275.19   172.1 2275.38
   174.6 2276.04  175.95 2276.78   180.6 2278.77   186.3 2279.15   195.4 2278.52
   200.5 2279.19   203.3 2280.41   211.9 2285.56   219.1 2291.49   226.6 2296.97
   237.9 2303.49   242.2 2306.32   247.4 2310.43     263 2319.37   273.6 2326.67
#Mann= 5 ,-1,0
       0      .1       0  116.78     .06       0   162.9    .045       0
  175.95     .06       0  186.78      .1       0
Bank Sta=162.9,175.95
XS Rating Curve= 0 ,0
Exp/Cntr(USF)=0,0
Exp/Cntr=0.5,0.3

Type RM Length L Ch R = 1 ,7874    ,98.9,99.4,100.4
XS GIS Cut Line= 3
2234047.80697993 455214.383617822233963.86323811454980.328714152
2233949.04963661 454921.07430816
#Sta/Elev= 30
       0 2311.16    13.2 2306.82    34.5 2298.51    44.4 2294.11    56.5 2289.57
    60.1 2288.58    90.5 2287.21      99 2288.64   103.3 2288.73   122.6 2287.53
   158.5 2286.08   162.8 2285.29     167 2283.71   175.8 2278.85   179.8 2277.63
   185.2 2276.84   188.3 2275.96   192.5 2275.62   196.8  2275.7   200.8 2277.12
   209.5  2278.6     235 2280.77   238.4 2282.15   241.5 2284.47   247.7 2289.97
   272.5  2307.8   276.6 2310.62   284.9 2315.37   293.1 2321.32   309.7 2331.41
#Mann= 4 ,-1,0
       0      .1       0    90.5     .06       0   185.2    .045       0
   200.8     .06       0
#XS Ineff= 2 , 0
             162  2285.6   215.5          2285.6
Permanent Ineff=
       F       F
Bank Sta=185.2,200.8
XS Rating Curve= 0 ,0
Exp/Cntr(USF)=0,0
Exp/Cntr=0.5,0.3

Type RM Length L Ch R = 1 ,7775    ,155,158.2,160.3
XS GIS Cut Line= 2
2234133.72586861455196.6072960222234045.83183306 454893.42225203
#Sta/Elev= 30
       0  2316.8    41.1 2299.86    45.2 2297.84    49.4 2294.73    53.5 2292.98
    57.7 2292.14    70.2 2291.94    78.5 2291.73   103.5 2288.79   107.7 2288.04
   120.2  2283.8   124.3 2283.14     141  2282.4   145.2 2281.63   157.7 2277.49
   163.6 2276.65   178.4 2276.28   184.8 2274.39   194.5 2273.66   211.8 2274.23
     216 2274.79   232.6 2282.22   236.8  2283.5   278.4  2289.5   286.8 2289.08
   288.1 2289.48   290.9 2290.74   294.6 2293.39   307.5 2303.67   315.7 2307.18
#Mann= 4 ,-1,0
       0      .1       0    70.2     .06       0   184.8    .045       0
   211.8     .06       0
#XS Ineff= 2 , 0
             168  2286.1     222         2285.73
Permanent Ineff=
       F       F
Bank Sta=184.8,211.8
XS Rating Curve= 0 ,0
Exp/Cntr(USF)=0,0
Exp/Cntr=0.5,0.3

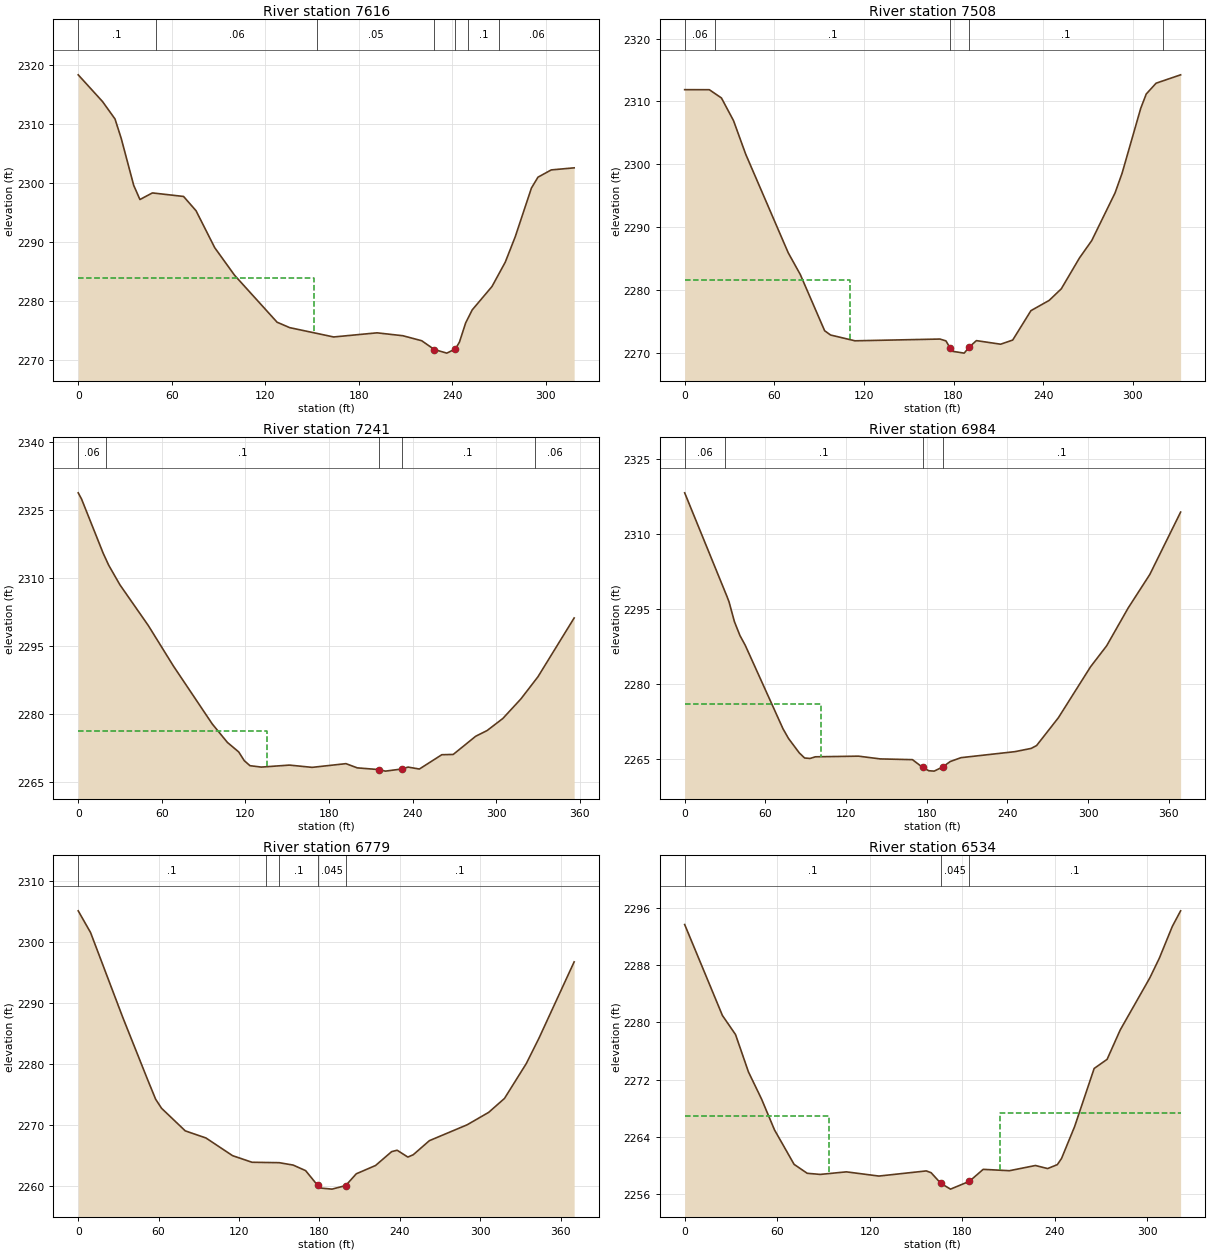
Type RM Length L Ch R = 1 ,7616    ,112,108.5,105
XS GIS Cut Line= 4
2234193.96784804455180.806121091 2234192.5206596455047.526638798
2234207.83011418454931.7866920512234185.90674075454867.284149106
#Sta/Elev= 30
       0 2318.39    15.6 2313.86    23.6 2310.91    27.6 2307.61    35.6 2299.66
    39.6 2297.25    47.6 2298.37    67.6 2297.77    75.6 2295.35    87.6 2289.08
   100.3 2284.42   127.6 2276.45   135.7 2275.53   163.9 2273.95   191.7 2274.65
   208.3 2274.16   220.4 2273.31   228.5 2271.82   236.5 2271.21     242 2271.92
   244.6 2273.08   248.6 2276.34   252.8 2278.54   265.5 2282.51     274 2286.63
   280.4 2290.94   290.8  2299.2     295 2301.04   303.5 2302.27   318.2 2302.62
#Mann= 7 ,-1,0
       0      .1       0      50     .06       0  153.29     .05       0
   228.5    .045       0     242     .05       0  250.04      .1       0
  270.04     .06       0
#XS Ineff= 2 , 0
          151.29 2284.01
Permanent Ineff=
       F       F
Bank Sta=228.5,242
XS Rating Curve= 0 ,0
Exp/Cntr(USF)=0,0
Exp/Cntr=0.3,0.1

Type RM Length L Ch R = 1 ,7508    ,266.2,267.4,266
XS GIS Cut Line= 2
2234342.32175931455149.3731671812234283.79888919454822.620475703
#Sta/Elev= 30
       0 2311.88    16.5 2311.87    24.6 2310.56    32.7 2306.95    40.8 2301.64
    69.3 2285.93    77.4 2282.46    93.7 2273.51    97.7 2272.83     114 2271.91
   170.9 2272.19   174.9  2271.9   177.8 2270.72     179 2270.25   187.1 2269.95
   190.6 2270.94   195.3 2271.94   211.5 2271.37   219.6 2272.03   231.8 2276.71
     244 2278.34   252.1 2280.18   264.3  2285.1   272.5 2287.86   288.1 2295.44
   292.8 2298.57   305.3 2308.91     309 2311.19   315.6 2312.91     332 2314.24
#Mann= 5 ,-1,0
       0     .06       0      20      .1       0   177.8    .045       0
   190.6      .1       0     320     .06       0
#XS Ineff= 2 , 0
          110.86  2281.6
Permanent Ineff=
       F       F
Bank Sta=177.8,190.6
XS Rating Curve= 0 ,0
Exp/Cntr(USF)=0,0
Exp/Cntr=0.3,0.1

Type RM Length L Ch R = 1 ,7241    ,253.1,256.6,259.7
XS GIS Cut Line= 3
2234559.07678268455150.7964785442234576.72524274455044.671514165
2234536.82917741454799.503894988
#Sta/Elev= 30
       0 2328.89     2.4 2327.52    17.9 2315.58    21.9 2312.91      30 2308.57
    50.3 2299.62    68.4 2290.65    96.2 2277.91   107.1 2273.82   115.2 2271.73
   119.2  2269.8   123.3 2268.69   131.4 2268.38   151.6 2268.82   167.9 2268.32
   192.2 2269.14   200.3 2268.21   215.7 2267.83   220.5 2267.49   232.1 2267.95
   236.8 2268.38   244.9 2267.95     261 2271.11   269.2 2271.17   285.3 2275.18
   293.5 2276.44   304.8  2279.1   317.8 2283.43     330  2288.3     356 2301.28
#Mann= 5 ,-1,0
       0     .06       0      20      .1       0   215.7    .045       0
   232.1      .1       0  327.58     .06       0
#XS Ineff= 2 , 0
          135.46 2276.38
Permanent Ineff=
       F       F
Bank Sta=215.7,232.1
XS Rating Curve= 0 ,0
Exp/Cntr(USF)=0,0
Exp/Cntr=0.3,0.1

Type RM Length L Ch R = 1 ,6984    ,204.1,204.5,204.7
XS GIS Cut Line= 2
  2234783.437349455154.1210407712234811.14132921454786.326820795
#Sta/Elev= 30
       0 2318.23    31.4 2297.57      33 2296.45      37  2292.5    41.1 2289.73
    45.1 2287.75    73.1 2271.12    77.2 2269.18    85.2  2266.3    89.2 2265.27
    93.2 2265.18    97.2 2265.51   129.3 2265.64   145.4 2265.09   169.4 2264.94
   176.9 2263.41   181.5 2262.73   185.5 2262.65  191.89 2263.48   197.5 2264.57
   205.5 2265.34   245.6 2266.54   257.7 2267.19   261.7 2267.76   277.9 2273.31
   301.8 2283.48   313.8 2287.68   329.8 2295.23   345.9 2301.93   368.8 2314.38
#Mann= 4 ,-1,0
       0     .06       0      30      .1       0   176.9    .045       0
  191.89      .1       0
#XS Ineff= 2 , 0
          101.59 2276.06
Permanent Ineff=
       F       F
Bank Sta=176.9,191.89
XS Rating Curve= 0 ,0
Exp/Cntr(USF)=0,0
Exp/Cntr=0.3,0.1

Type RM Length L Ch R = 1 ,6779    ,250.9,245.7,239
XS GIS Cut Line= 3
 2234911.5999268455152.8110669642234996.67163845455026.287908512
 2235017.3360225454809.657256999
#Sta/Elev= 30
       0 2305.14     9.2 2301.59    33.3 2287.66      52 2277.38    57.8 2274.28
    62.2  2272.8    79.9  2269.1    95.3 2267.94   115.2 2265.04   129.7 2263.96
     150 2263.89   160.4  2263.5   169.7 2262.59   178.7 2260.17   181.7 2259.72
   189.4 2259.56  199.62 2260.14   207.5 2262.07   221.9 2263.43   233.9  2265.7
     238 2265.93     246 2264.81     250 2265.19   262.1  2267.5   290.2 2270.09
   306.3 2272.13   318.1 2274.41   334.4 2280.13   343.8 2284.26   370.1 2296.78
#Mann= 5 ,-1,0
       0      .1       0     140     .06       0     150      .1       0
   178.7    .045       0  199.62      .1       0
Bank Sta=178.7,199.62
XS Rating Curve= 0 ,0
Exp/Cntr(USF)=0,0
Exp/Cntr=0.3,0.1

Type RM Length L Ch R = 1 ,6534    ,196.6,201.6,203.7
XS GIS Cut Line= 2
2235276.33413998455080.3425798442235171.51490618454776.124861344
#Sta/Elev= 30
       0 2293.72    24.5 2280.98      33 2278.31    41.4 2273.07    49.9 2269.27
    58.3 2264.95      71 2260.13    79.5 2258.88      88 2258.72   104.9 2259.08
     126 2258.49   156.8 2259.21   159.9 2258.96   166.2 2257.47   172.5 2256.66
   184.7 2257.75   193.7 2259.43   210.7 2259.24   227.6 2259.97   235.5 2259.54
   241.8 2260.09   244.5 2260.94     253 2265.41   265.7 2273.56   274.1 2274.84
   282.6 2278.95   301.8 2286.24     308 2289.01   316.4 2293.45   321.8 2295.64
#Mann= 3 ,-1,0
       0      .1       0   166.2    .045       0   184.7      .1       0
#XS Ineff= 2 , 0
           93.77 2266.93  204.28         2267.38
Permanent Ineff=
       F       F
Bank Sta=166.2,184.7
XS Rating Curve= 0 ,0
Exp/Cntr(USF)=0,0
Exp/Cntr=0.3,0.1

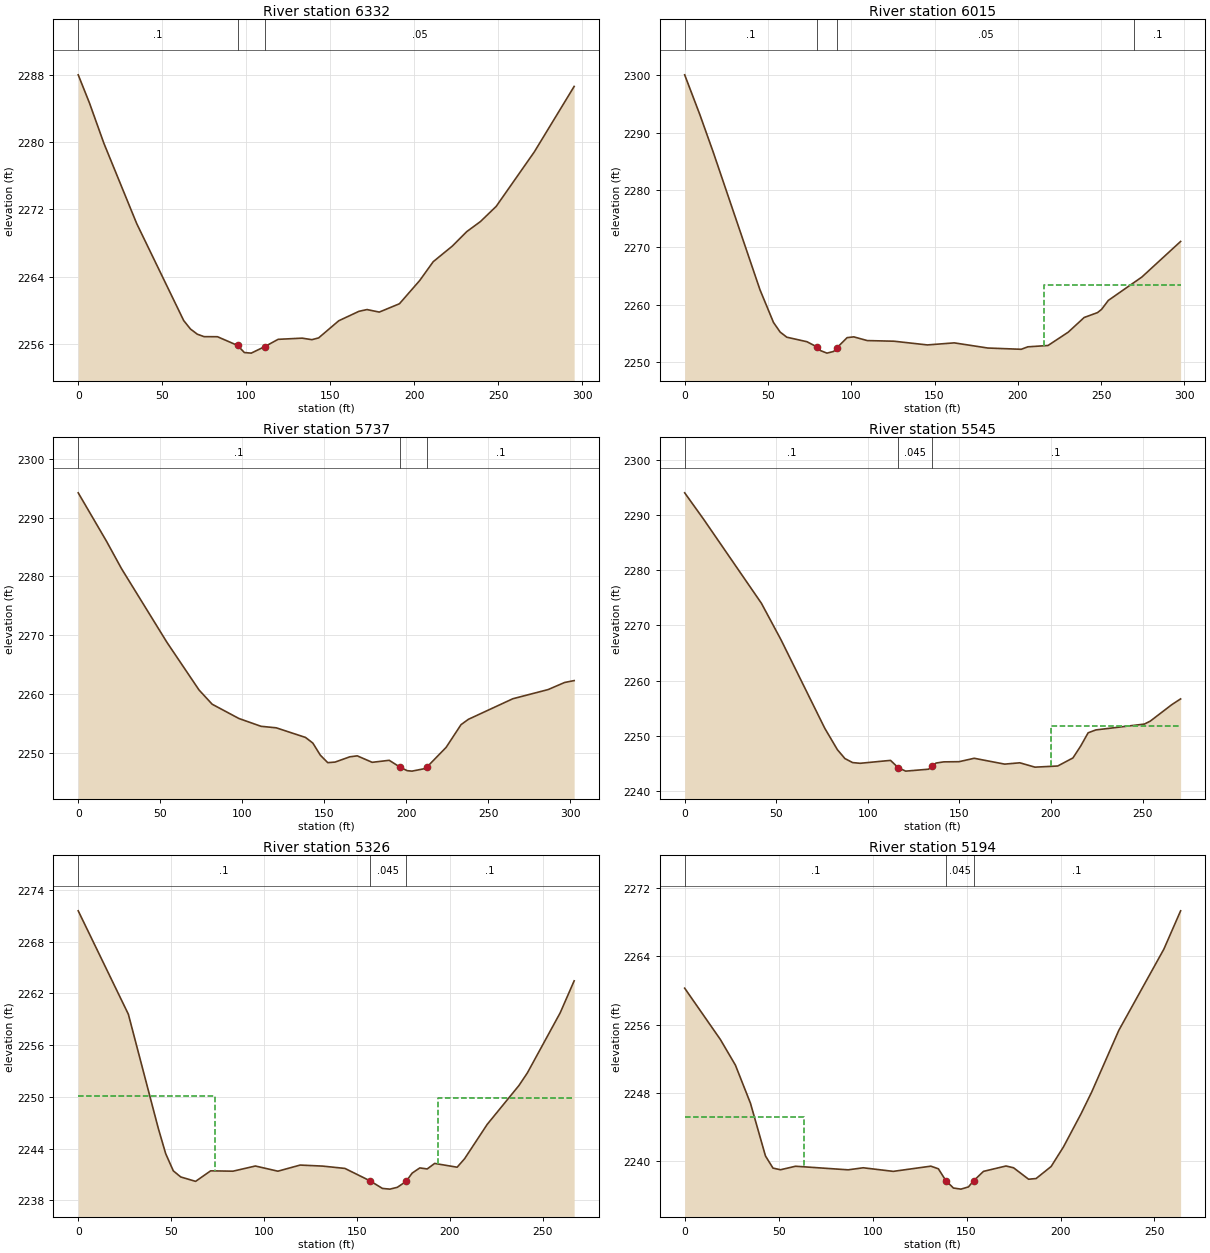
Type RM Length L Ch R = 1 ,6332    ,314.8,316.7,315
XS GIS Cut Line= 2
2235408.70599093455035.8266068922235385.99180196454741.529723799
#Sta/Elev= 30
       0 2287.98     6.7 2284.63    15.3 2279.83    34.8  2270.3    62.8 2258.76
    66.8 2257.76    70.9 2257.14    74.9 2256.85    82.9 2256.84    94.9  2255.8
    98.9 2254.96     103 2254.89     111 2255.66     119 2256.53   133.3 2256.67
   139.1 2256.49   143.1  2256.7   155.1 2258.74   167.1 2259.86   171.9 2260.07
   179.2 2259.77   191.2 2260.76   203.3 2263.53   211.3 2265.76   222.7 2267.62
   231.3 2269.34   239.4 2270.53   248.8 2272.34   271.5 2278.82   295.2  2286.6
#Mann= 3 ,-1,0
       0      .1       0    94.9    .045       0     111     .05       0
Bank Sta=94.9,111
XS Rating Curve= 0 ,0
Exp/Cntr(USF)=0,0
Exp/Cntr=0.3,0.1

Type RM Length L Ch R = 1 ,6015    ,271,278,286.6
XS GIS Cut Line= 2
2235670.41295072455006.1994038972235640.78574773454709.927373937
#Sta/Elev= 30
       0 2300.11     9.1 2293.17    17.1 2286.65    45.2  2262.6    53.3  2256.9
    57.3 2255.22    61.3 2254.32    73.4 2253.53   79.28 2252.64    81.4    2252
    85.4 2251.54    89.5 2251.84   91.43 2252.48    97.5 2254.24   101.5 2254.38
   109.6 2253.73   125.6 2253.62   145.7 2252.97   161.8 2253.33     182 2252.43
     202 2252.21     206 2252.64   218.1 2252.87   230.2 2255.19   239.8 2257.76
   247.8 2258.61   250.3 2259.19   254.3 2260.74   274.4 2264.81   297.7 2271.03
#Mann= 4 ,-1,0
       0      .1       0   79.28    .045       0   91.43     .05       0
     270      .1       0
#XS Ineff= 2 , 0
                          215.78         2263.46
Permanent Ineff=
       F       F
Bank Sta=79.28,91.43
XS Rating Curve= 0 ,0
Exp/Cntr(USF)=0,0
Exp/Cntr=0.3,0.1

Type RM Length L Ch R = 1 ,5737    ,195.4,192.8,189.7
XS GIS Cut Line= 3
2235809.66080481454978.5473477672235800.77264391454882.752724747
2235896.56726693454700.051639605
#Sta/Elev= 30
       0  2294.2    17.4 2285.89    26.4  2281.3    54.1 2268.76    73.7 2260.64
    81.7 2258.22      98 2255.79   111.5 2254.46   120.8  2254.2   138.6 2252.57
   143.1 2251.61   147.7 2249.54   152.2 2248.27   156.7 2248.37   165.7 2249.27
   170.2 2249.43   179.3 2248.33   189.7 2248.67   196.3 2247.51   200.6 2246.91
   203.6 2246.83   210.9 2247.23  212.91 2247.58   224.4 2250.87   233.5 2254.74
     238 2255.65   265.1 2259.15   286.6 2260.71   296.7 2261.92   302.5 2262.24
#Mann= 3 ,-1,0
       0      .1       0   196.3    .045       0  212.91      .1       0
Bank Sta=196.3,212.91
XS Rating Curve= 0 ,0
Exp/Cntr(USF)=0,0
Exp/Cntr=0.3,0.1

Type RM Length L Ch R = 1 ,5545    ,220,218.8,215.5
XS GIS Cut Line= 2
2235987.77666695454993.5538734872236059.94148643454732.590956625
#Sta/Elev= 30
       0 2294.04    10.4 2289.22    41.9 2274.01    52.6 2267.39    76.5 2251.34
    83.4 2247.45    87.5 2245.85    91.7 2245.12    95.8 2244.99   112.4 2245.52
   116.6 2244.19   120.7 2243.57   133.2 2243.92  134.88 2244.41   137.3 2245.04
   141.5 2245.25   149.8 2245.28   158.1  2245.9   174.7 2244.84     183 2245.08
   191.3 2244.29   203.7  2244.5     212 2245.96   216.2  2248.1   220.3 2250.52
   224.5 2251.04     251  2252.1   254.2 2252.63     266 2255.63   270.8 2256.67
#Mann= 3 ,-1,0
       0      .1       0   116.6    .045       0  134.88      .1       0
#XS Ineff= 2 , 0
                           200.2          2251.7
Permanent Ineff=
       F       F
Bank Sta=116.6,134.88
XS Rating Curve= 0 ,0
Exp/Cntr(USF)=0,0
Exp/Cntr=0.3,0.1

Type RM Length L Ch R = 1 ,5326    ,132.6,132.1,131.2
XS GIS Cut Line= 3
 2236213.2644492455012.0546761592236236.47074098454789.023726672
2236254.72385614454750.397726185
#Sta/Elev= 30
       0 2271.56      27 2259.57    43.1 2246.35    47.1  2243.4    51.2 2241.41
    55.2  2240.7    63.2 2240.19    71.3 2241.41    83.3 2241.37    95.4 2241.97
   107.5 2241.37   119.5 2242.08   131.6 2241.96   143.6 2241.69   157.1 2240.25
   163.8 2239.37   167.8 2239.29   171.8  2239.5   176.5 2240.18   179.8 2241.15
   183.9 2241.75   187.9 2241.63   191.9 2242.27     204 2241.83     208 2242.81
   220.2  2246.8   237.3 2251.31   241.8 2252.76   259.5 2259.74     267 2263.44
#Mann= 3 ,-1,0
       0      .1       0   157.1    .045       0   176.5      .1       0
#XS Ineff= 2 , 0
            73.8 2250.11  193.92         2249.89
Permanent Ineff=
       F       F
Bank Sta=157.1,176.5
XS Rating Curve= 0 ,0
Exp/Cntr(USF)=0,0
Exp/Cntr=0.3,0.1

Type RM Length L Ch R = 1 ,5194    ,161.8,160.4,162.8
XS GIS Cut Line= 3
2236355.97274704455020.2034611622236357.76406023454797.821409491
2236358.29830794454756.343325297
#Sta/Elev= 30
       0 2260.26      19 2254.25      27 2251.25      35 2246.79      43 2240.61
      47 2239.19      51    2239      59 2239.41      87 2238.99      95 2239.23
     111 2238.81     131 2239.42     135 2239.11     139 2237.72     143 2236.86
     147 2236.73     151 2236.99  153.77 2237.71     159 2238.81     171 2239.44
     175 2239.23     183 2237.89     187 2237.97     195 2239.38   201.6 2241.69
     211 2245.59   216.6 2248.11     231 2255.32     255 2264.84   263.9 2269.32
#Mann= 3 ,-1,0
       0      .1       0     139    .045       0  153.77      .1       0
#XS Ineff= 2 , 0
           63.35 2245.12
Permanent Ineff=
       F       F
Bank Sta=139,153.77
XS Rating Curve= 0 ,0
Exp/Cntr(USF)=0,0
Exp/Cntr=0.3,0.1