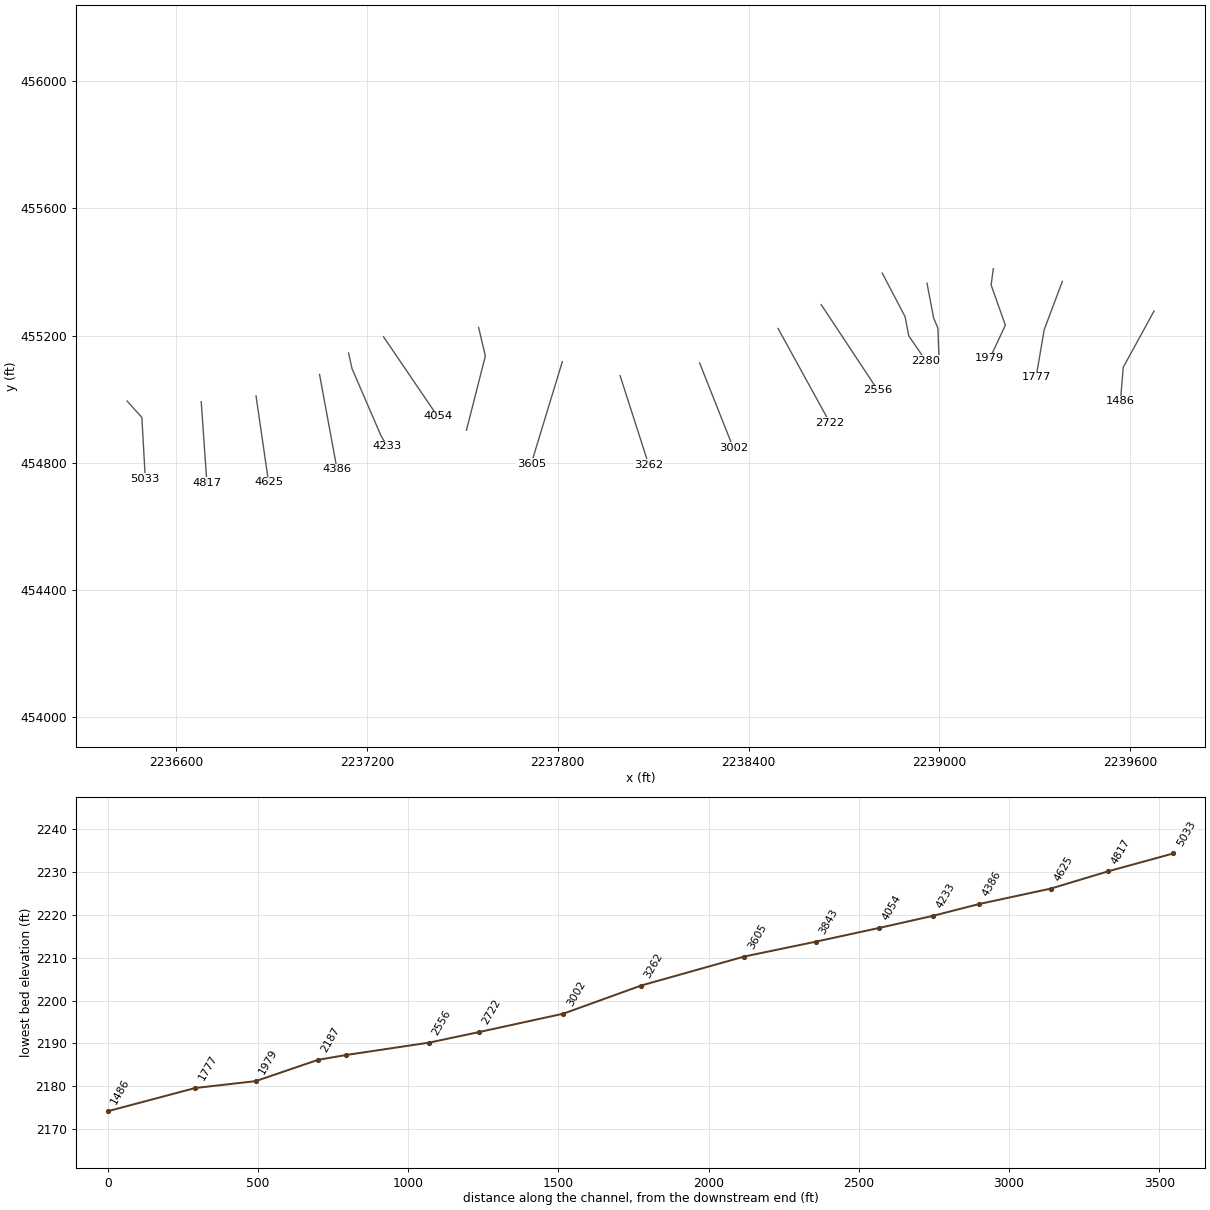
HEC-RAS study BRSHLCKRN.prj: BRSHLCKRN

--- BRSHLCKRN.g01 (geometry) --- (continued)

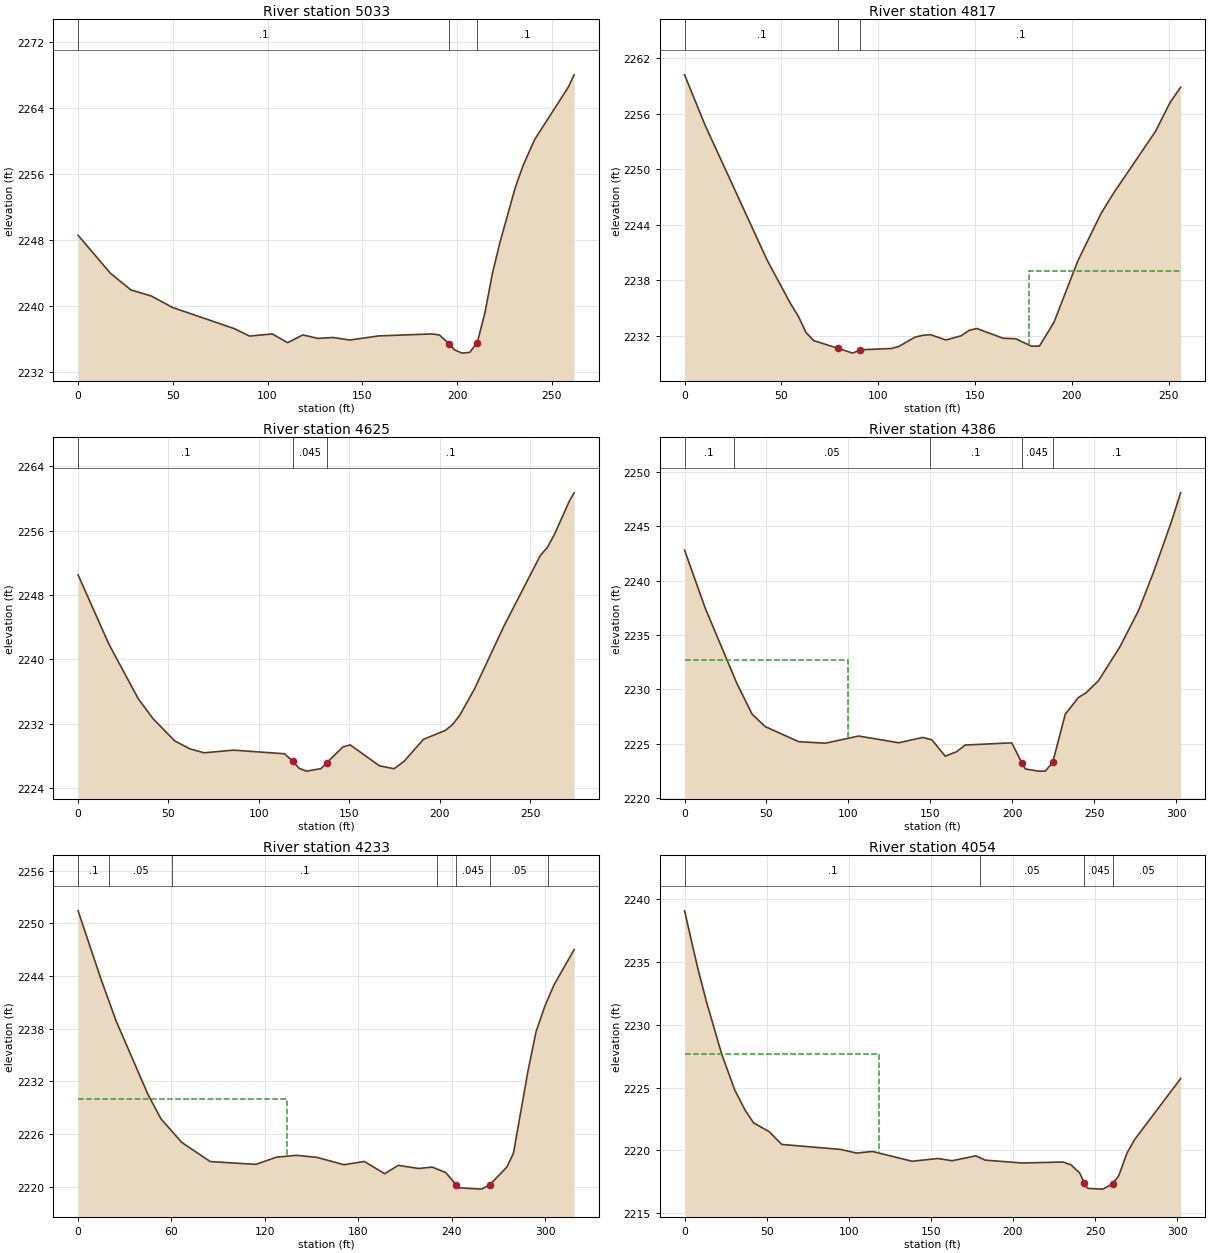
Type RM Length L Ch R = 1 ,5033    ,216.6,216.6,218.1
XS GIS Cut Line= 3
2236446.39864409454993.8929631612236492.67947549454942.550165824
2236503.52654535454750.195460309
#Sta/Elev= 30
       0 2248.59    17.1 2243.97    27.9 2241.95    38.7 2241.21    49.9 2239.82
    82.5 2237.25    90.5 2236.35   102.5 2236.61   110.6 2235.55   118.6 2236.49
   126.6 2236.07   134.6 2236.18   143.3 2235.87   158.6 2236.37   186.7 2236.61
   190.7 2236.49  195.98 2235.36   198.7 2234.67   202.7 2234.28   206.7 2234.37
   210.3 2235.46   210.7 2235.58   214.7 2239.17   218.7    2244   222.7 2247.77
   230.8 2254.44   234.8 2257.02   240.9 2260.19   258.8 2266.61   261.8 2268.07
#Mann= 3 ,-1,0
       0      .1       0  195.98    .045       0   210.3      .1       0
Bank Sta=195.98,210.3
XS Rating Curve= 0 ,0
Exp/Cntr(USF)=0,0
Exp/Cntr=0.3,0.1

Type RM Length L Ch R = 1 ,4817    ,189,191.8,193.1
XS GIS Cut Line= 2
2236679.34299206454991.7582009242236697.09806369454736.276035227
#Sta/Elev= 30
       0 2260.19    10.6 2254.75    42.7 2240.14    54.7 2235.47    58.7 2234.12
    62.7 2232.35    66.7 2231.47    79.4 2230.63    86.8 2230.12    90.8 2230.48
   106.8 2230.62   110.8 2230.86   118.9 2231.84   122.9 2232.04   126.9 2232.12
   134.9 2231.54   142.9    2232   146.9 2232.58   150.9 2232.78   164.4 2231.73
     171 2231.67     179 2230.88   183.2 2230.88   190.7 2233.44   203.1 2240.12
   215.1 2245.24   221.6 2247.44   243.2  2254.1   250.6 2257.18   256.1 2258.85
#Mann= 3 ,-1,0
       0      .1       0    79.4    .045       0    90.8      .1       0
#XS Ineff= 2 , 0
                          177.91         2238.96
Permanent Ineff=
       F       F
Bank Sta=79.4,90.8
XS Rating Curve= 0 ,0
Exp/Cntr(USF)=0,0
Exp/Cntr=0.3,0.1

Type RM Length L Ch R = 1 ,4625    ,237.1,239.2,238.3
XS GIS Cut Line= 2
2236851.55077683455010.1496976292236891.05371416  454738.5670035
#Sta/Elev= 30
       0 2250.49    17.1 2241.85    33.3 2235.08    41.4 2232.62    53.5 2229.83
    61.9 2228.85    69.7 2228.36    85.9 2228.69   114.2 2228.24   118.7 2227.33
   122.2 2226.44   126.3 2226.08   134.4 2226.39   137.6 2227.14   146.5 2229.09
   150.5 2229.35   166.7 2226.74   174.8 2226.38   180.2 2227.27     191 2230.03
   203.1 2231.14   207.1 2231.86   211.2 2233.06   219.3 2236.31   235.4 2244.05
   255.6 2252.87   259.7 2253.95   263.7 2255.62   271.8  2259.7   274.4  2260.7
#Mann= 3 ,-1,0
       0      .1       0   118.7    .045       0   137.6      .1       0
Bank Sta=118.7,137.6
XS Rating Curve= 0 ,0
Exp/Cntr(USF)=0,0
Exp/Cntr=0.3,0.1

Type RM Length L Ch R = 1 ,4386    ,148.5,152.5,155.2
XS GIS Cut Line= 2
2237051.22966073455077.6769873932237106.24207845454779.888513115
#Sta/Elev= 30
       0 2242.81    12.7 2237.44    32.1 2230.49    41.2 2227.72    49.3 2226.56
    69.7 2225.18    85.9 2225.04   106.3  2225.7   130.7 2225.08   145.4 2225.57
     151 2225.35   159.1 2223.85     166 2224.25   171.3 2224.87     199 2225.07
   199.8 2225.05  205.95 2223.22     208 2222.67   216.1 2222.47   220.2 2222.47
  224.71 2223.27   232.4 2227.71   240.5 2229.26     245 2229.67   252.7  2230.8
   265.6 2233.87   277.1 2237.24   286.2 2240.75   297.4 2245.52   302.8 2248.08
#Mann= 5 ,-1,0
       0      .1       0      30     .05       0     150      .1       0
  205.95    .045       0  224.71      .1       0
#XS Ineff= 2 , 0
          100.05 2232.66
Permanent Ineff=
       F       F
Bank Sta=205.95,224.71
XS Rating Curve= 0 ,0
Exp/Cntr(USF)=0,0
Exp/Cntr=0.3,0.1

Type RM Length L Ch R = 1 ,4233    ,176.7,179.6,182.2
XS GIS Cut Line= 4
2237142.54958638455144.9606642092237153.39665624455095.787280844
2237245.23518106 454883.18471159 2237264.7599068454852.089777992
#Sta/Elev= 30
       0 2251.44    14.6 2243.72    24.4 2238.91    44.8 2230.56    53.2 2227.76
    66.6 2225.06    84.9 2222.88   114.2 2222.56   127.5 2223.38   140.3 2223.59
   153.4 2223.36   170.8 2222.52   183.9 2222.89     197  2221.5   205.7 2222.45
   218.8 2222.09   227.5 2222.25   236.2 2221.63   243.1 2220.19   244.9 2219.89
   259.1 2219.74   264.4 2220.22   275.4 2222.24   279.3 2223.67   279.8 2223.93
     289 2233.16   294.2 2237.66     300 2240.64   305.8 2243.02   318.7 2247.03
#Mann= 7 ,-1,0
       0      .1       0      20     .05       0   60.36      .1       0
  230.36     .05       0   243.1    .045       0   264.4     .05       0
  301.95      .1       0
#XS Ineff= 2 , 0
          134.21 2229.96
Permanent Ineff=
       F       F
Bank Sta=243.1,264.4
XS Rating Curve= 0 ,0
Exp/Cntr(USF)=0,0
Exp/Cntr=0.3,0.1

Type RM Length L Ch R = 1 ,4054    ,223.8,210.8,198.1
XS GIS Cut Line= 2
2237252.50559071455195.8135030712237422.36822122454945.957424471
#Sta/Elev= 30
       0 2239.07       8 2234.53    13.2  2231.9    22.5 2227.71    30.5 2224.82
      37 2223.17      42 2222.19    51.6 2221.48    59.2 2220.47    95.1 2220.07
   104.8 2219.78   114.4 2219.91   138.6 2219.13   154.3 2219.35   162.9 2219.17
   177.4 2219.56   183.1 2219.22   205.7 2218.99   230.5 2219.07   235.4 2218.84
   240.6  2218.2   243.5 2217.41     245 2217.03   246.4 2216.96   254.7 2216.91
   260.8 2217.34   264.4 2217.97   269.4 2219.76     274 2220.84   302.1 2225.71
#Mann= 4 ,-1,0
       0      .1       0     180     .05       0   243.5    .045       0
   260.8     .05       0
#XS Ineff= 2 , 0
          118.53 2227.63
Permanent Ineff=
       F       F
Bank Sta=243.5,260.8
XS Rating Curve= 0 ,0
Exp/Cntr(USF)=0,0
Exp/Cntr=0.3,0.1

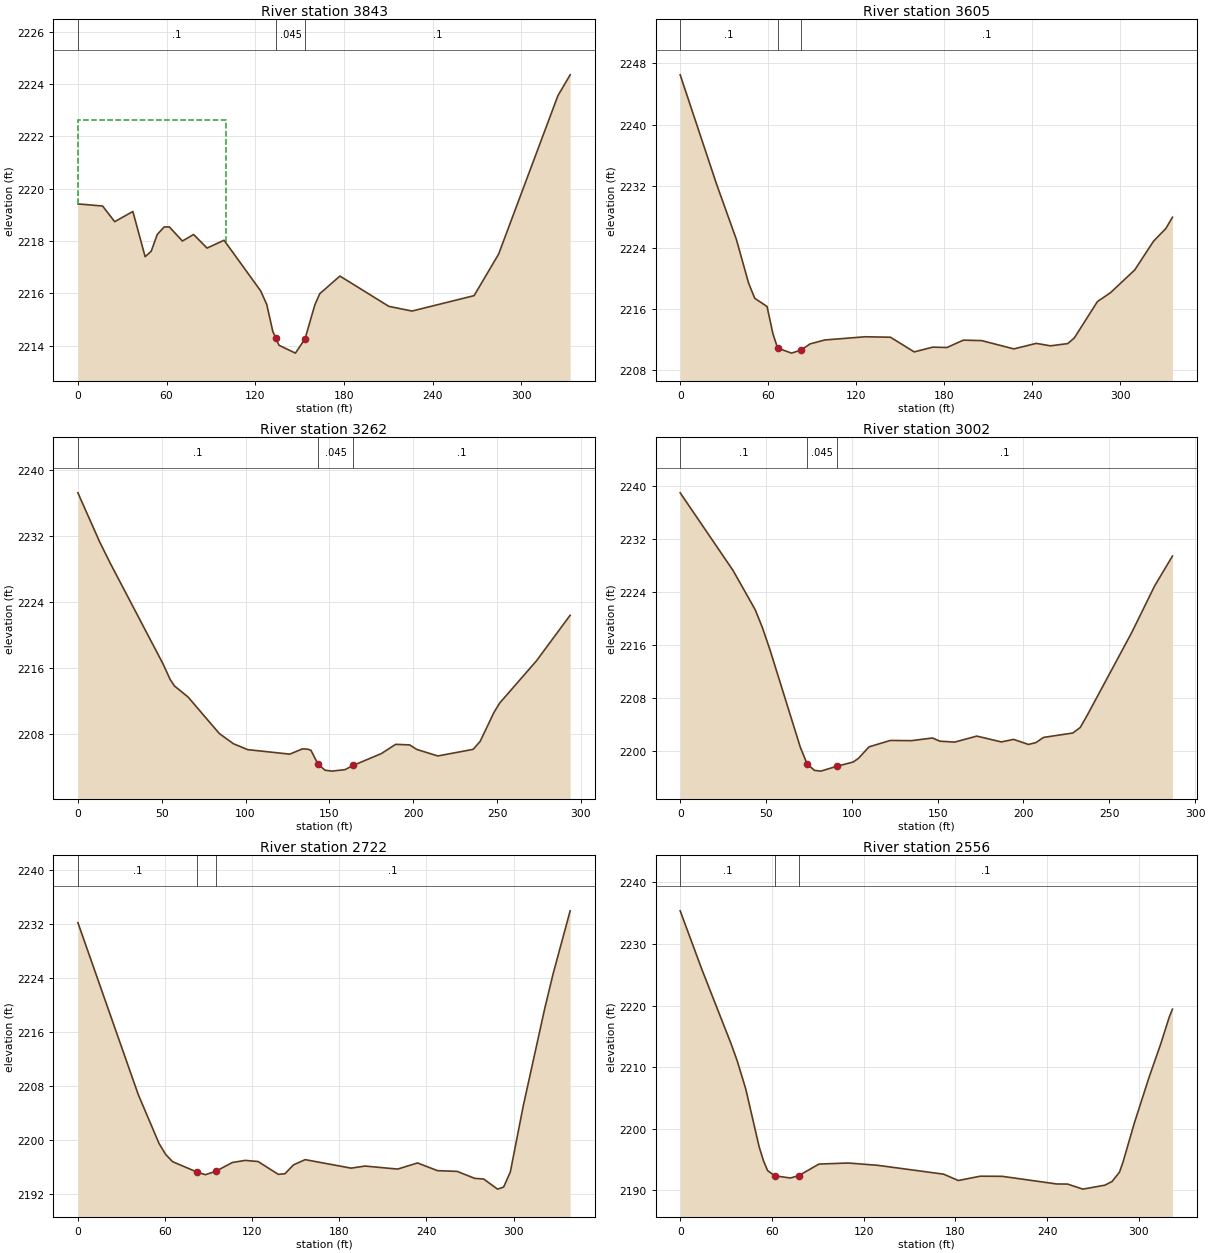
Type RM Length L Ch R = 1 ,3843    ,237.5,238,236.6
XS GIS Cut Line= 3
2237551.31117386  455225.41627532237572.50178315455135.713555453
2237513.07482473454902.275103832
#Sta/Elev= 30
       0 2219.42    16.7 2219.34    24.9 2218.74    37.2 2219.13    45.5  2217.4
    49.6 2217.61    53.7 2218.25    58.4 2218.54    61.9 2218.54    70.7    2218
    78.3 2218.25    87.4 2217.73    98.9 2218.03   123.7 2216.09   127.8 2215.57
   131.9 2214.54     134 2214.27     134 2214.26   136.1 2214.01   147.2 2213.71
   153.7 2214.26   160.3 2215.55   163.6 2215.98   177.3 2216.66   210.4  2215.5
   226.1 2215.32   268.1 2215.91   284.7  2217.5   324.8 2223.56   333.1 2224.36
#Mann= 3 ,-1,0
       0      .1       0     134    .045       0   153.7      .1       0
#XS Ineff= 2 , 0
          100.05 2222.62
Permanent Ineff=
       F       F
Bank Sta=134,153.7
XS Rating Curve= 0 ,0
Exp/Cntr(USF)=0,0
Exp/Cntr=0.3,0.1

Type RM Length L Ch R = 1 ,3605    ,333.2,343.3,352.5
XS GIS Cut Line= 2
 2237814.4348742455117.7952018482237716.66510431454796.833836058
#Sta/Elev= 30
       0 2246.48    24.7  2232.3    38.3 2225.05    46.6 2219.38    50.8 2217.39
    59.2 2216.32    63.2 2212.78    66.4 2210.91    75.9 2210.25    82.4 2210.66
    88.5 2211.45    98.5 2211.96   126.1 2212.38   143.3 2212.32   159.5 2210.41
   172.2 2211.03   181.8 2210.98     193 2211.94   205.5 2211.88   227.4  2210.8
   242.7 2211.52   252.3  2211.2   264.1 2211.49   268.6 2212.22   284.4 2216.97
   293.3 2218.12   309.8 2221.08   322.6 2224.82     331 2226.47   335.5 2227.94
#Mann= 3 ,-1,0
       0      .1       0    66.4    .045       0    82.4      .1       0
Bank Sta=66.4,82.4
XS Rating Curve= 0 ,0
Exp/Cntr(USF)=0,0
Exp/Cntr=0.3,0.1

Type RM Length L Ch R = 1 ,3262    ,258,259.2,260.3
XS GIS Cut Line= 2
2237996.07169818455073.542413237 2238085.9408806454794.059131642
#Sta/Elev= 30
       0 2237.25      13 2231.29    19.4 2228.67    50.8 2216.49      55 2214.62
    57.6 2213.82    65.7 2212.48    84.4 2208.04    92.8 2206.81   101.2  2206.1
   126.4 2205.55   133.9 2206.19   137.1 2206.15     139 2206.02   143.12204.373
   147.4  2203.6   151.6 2203.49   159.3 2203.67   164.2 2204.18   181.1 2205.63
   189.5 2206.74   197.9 2206.67   202.1 2206.12   214.7 2205.33   235.7 2206.13
   239.9 2207.09   248.1 2210.59   251.5 2211.73   273.5 2216.87   293.6  2222.4
#Mann= 3 ,-1,0
       0      .1       0   143.1    .045       0   164.2      .1       0
Bank Sta=143.1,164.2
XS Rating Curve= 0 ,0
Exp/Cntr(USF)=0,0
Exp/Cntr=0.3,0.1

Type RM Length L Ch R = 1 ,3002    ,279.1,280.4,282.1
XS GIS Cut Line= 2
2238246.00446451455113.8449081152238351.67482186454847.200081151
#Sta/Elev= 30
       0 2239.04    30.8 2227.29    43.7 2221.36      48 2218.58    52.3  2215.3
      70 2200.54    73.9 2198.04    78.2 2197.05    81.9 2196.93    91.5 2197.68
   100.8 2198.31   103.9 2198.87     110  2200.6   122.4 2201.57   134.7 2201.54
     147 2201.94   151.3 2201.46   159.9 2201.32   172.8 2202.23   187.1 2201.35
   194.3 2201.73   202.9 2200.97   207.2 2201.24   211.7 2202.03   228.8  2202.7
   233.1 2203.54   237.4  2205.5   263.2 2217.96   276.4 2224.94   286.8 2229.47
#Mann= 3 ,-1,0
       0      .1       0    73.9    .045       0    91.5      .1       0
Bank Sta=73.9,91.5
XS Rating Curve= 0 ,0
Exp/Cntr(USF)=0,0
Exp/Cntr=0.3,0.1

Type RM Length L Ch R = 1 ,2722    ,165,165.9,166.5
XS GIS Cut Line= 2
2238492.69490899455222.1768778542238655.85070209454925.042464191
#Sta/Elev= 30
       0 2232.15    41.6 2206.65    55.9 2199.41    60.5 2197.78    65.2 2196.72
      82 2195.18    87.8 2194.79    94.9 2195.29   106.4  2196.6   115.2 2196.91
   124.1 2196.74     138 2194.84   142.6 2194.93   148.5 2196.25   156.5 2197.02
   188.2 2195.76   197.7 2196.07   220.2 2195.62   233.9 2196.53   247.6 2195.39
   261.2 2195.28   273.2 2194.25   279.5 2194.14     289 2192.65   293.2 2192.96
   297.8 2195.19   306.7 2204.98   321.4 2219.33   327.3  2224.6     339  2233.9
#Mann= 3 ,-1,0
       0      .1       0      82    .045       0    94.9      .1       0
Bank Sta=82,94.9
XS Rating Curve= 0 ,0
Exp/Cntr(USF)=0,0
Exp/Cntr=0.3,0.1

Type RM Length L Ch R = 1 ,2556    ,270.6,276,265.9
XS GIS Cut Line= 2
2238628.38850856  455296.87409682238805.98559676455028.331847052
#Sta/Elev= 30
       0 2235.38    14.1 2225.92    33.2 2213.85    37.2 2211.09    42.9 2206.45
    51.6 2197.11    54.5 2194.78    57.2 2193.19      62 2192.34    72.1    2192
    77.6 2192.39    90.8 2194.26   109.9 2194.43   129.1 2194.06   172.3 2192.62
   181.9 2191.59   196.3 2192.29   210.6 2192.27   246.2 2191.03   253.4 2191.01
   263.4 2190.19   277.8 2190.83   282.5 2191.43   287.4 2192.96   289.7 2194.61
     297 2200.86   306.6 2208.27   314.3 2213.74     320 2218.19     322 2219.41
#Mann= 3 ,-1,0
       0      .1       0      62    .045       0    77.6      .1       0
Bank Sta=62,77.6
XS Rating Curve= 0 ,0
Exp/Cntr(USF)=0,0
Exp/Cntr=0.3,0.1

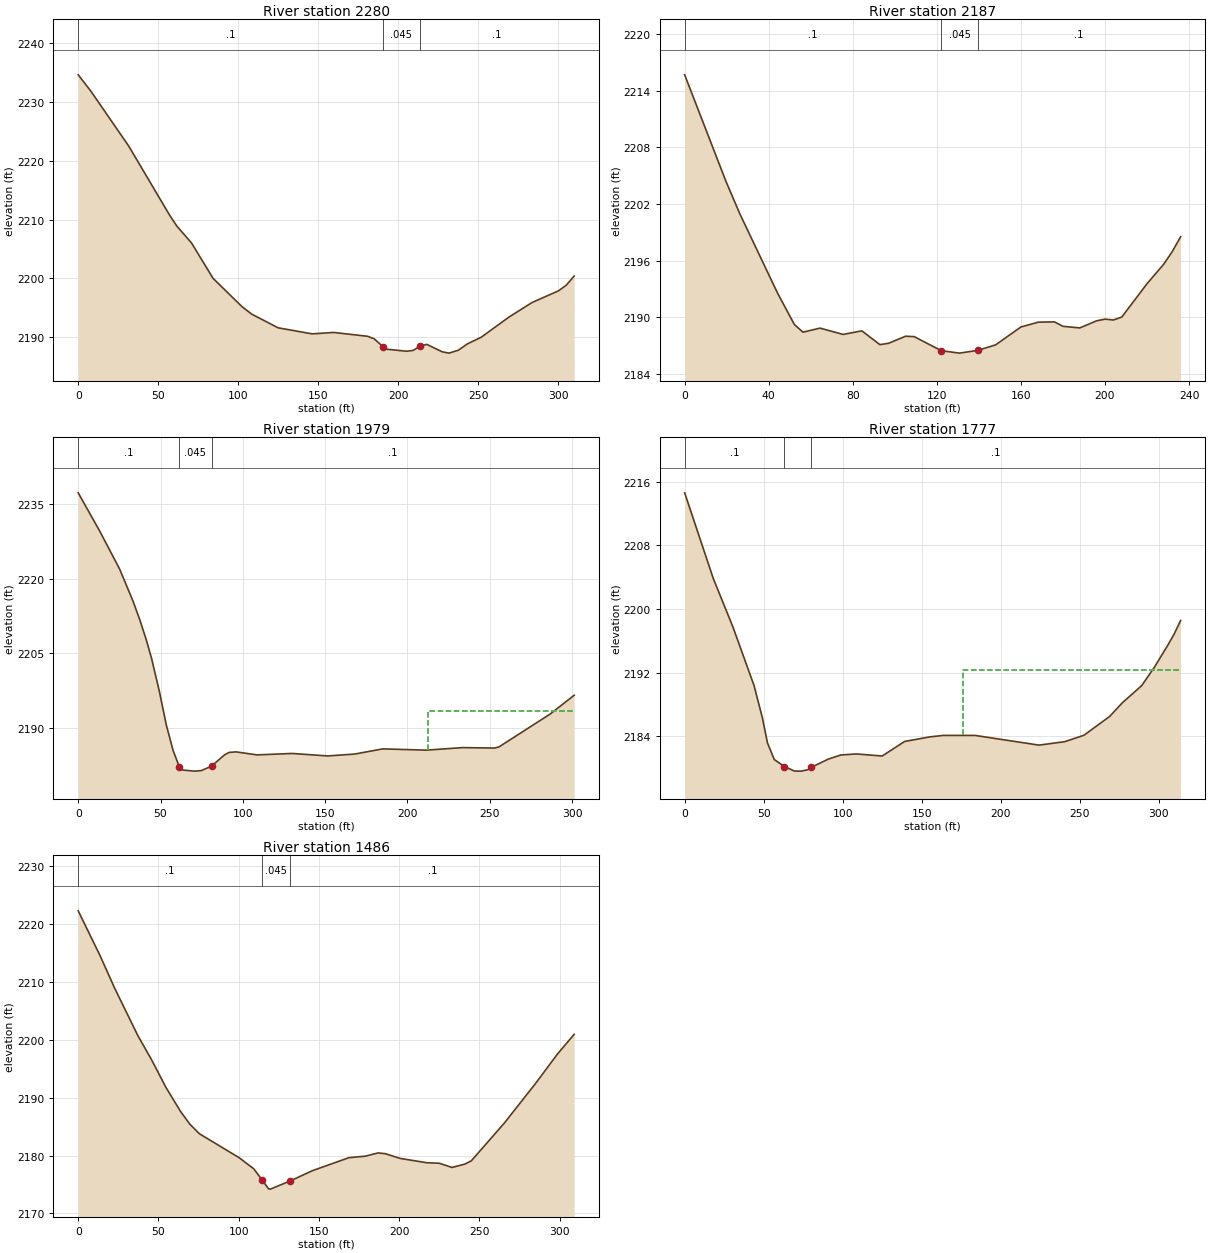
Type RM Length L Ch R = 1 ,2280    ,89.1,93.2,94.1
XS GIS Cut Line= 4
2238820.33121045455395.8529136462238891.81938035455259.425260141
2238903.62096415   455198.8089372238956.80543448455121.112830985
#Sta/Elev= 30
       0 2234.57     7.8 2231.84    31.5  2222.5    57.2  2210.7    61.7 2208.86
    70.8 2206.02    84.3    2200   102.4 2195.19   108.5 2193.92   124.9 2191.61
   146.2 2190.58   159.7 2190.82   180.8 2190.17   184.8 2189.77   190.4 2188.43
     193 2187.97   205.2 2187.63   209.3 2187.77   213.4 2188.47   217.8  2188.8
   227.4 2187.54   231.7 2187.31   237.5  2187.8   243.2 2188.88   251.9 2190.02
   269.1 2193.42   283.5 2195.89   300.2  2197.9     305 2198.86   309.9  2200.4
#Mann= 3 ,-1,0
       0      .1       0   190.4    .045       0   213.4      .1       0
Bank Sta=190.4,213.4
XS Rating Curve= 0 ,0
Exp/Cntr(USF)=0,0
Exp/Cntr=0.3,0.1

Type RM Length L Ch R = 1 ,2187    ,209.4,208.6,207.3
XS GIS Cut Line= 4
2238960.82546101455364.4658083792238981.72394989455254.896707335
2238995.05054744455223.3015832322238998.33698463455133.153492976
#Sta/Elev= 30
       0 2215.67    19.6 2204.41    26.2 2200.97    44.1 2192.59    52.2 2189.22
    56.3 2188.41    64.4 2188.84    75.4 2188.17    84.3 2188.55    92.9 2187.09
      97 2187.23   105.1 2187.98   109.2 2187.94   122.1 2186.45   130.8 2186.19
   139.5 2186.48     148 2187.07     160 2188.96   168.3 2189.47     176  2189.5
     180 2189.03     188 2188.86     196 2189.61     200 2189.79     204  2189.7
     208 2190.01     220 2193.54     228 2195.62     232 2196.94     236 2198.51
#Mann= 3 ,-1,0
       0      .1       0   122.1    .045       0   139.5      .1       0
Bank Sta=122.1,139.5
XS Rating Curve= 0 ,0
Exp/Cntr(USF)=0,0
Exp/Cntr=0.3,0.1

Type RM Length L Ch R = 1 ,1979    ,211.4,201.2,190.9
XS GIS Cut Line= 4
2239169.28506726455410.1172910052239162.45487218455358.746726404
2239207.18321422455232.3623972982239158.10262455455127.917917771
#Sta/Elev= 30
       0 2237.29    13.1 2229.56    25.2  2221.9    33.2 2215.55    37.3 2211.82
    41.3 2207.74    44.6 2203.88    49.4 2197.14    53.5 2190.54    57.7 2185.31
   61.38 2182.13      62 2181.64    63.8 2181.42    70.5 2181.21    74.7 2181.31
      81 2182.21    88.9 2184.49    91.7 2184.98    95.9 2185.09   108.6 2184.48
   129.9 2184.77   151.6 2184.27     168 2184.65     185 2185.69   211.6 2185.44
   233.6 2185.95     253 2185.86   255.7  2186.1   286.8 2192.73   301.3  2196.5
#Mann= 3 ,-1,0
       0      .1       0   61.38    .045       0      81      .1       0
#XS Ineff= 2 , 0
                          212.79         2193.32
Permanent Ineff=
       F       F
Bank Sta=61.38,81
XS Rating Curve= 0 ,0
Exp/Cntr(USF)=0,0
Exp/Cntr=0.3,0.1

Type RM Length L Ch R = 1 ,1777    ,292.5,290.9,288.9
XS GIS Cut Line= 3
2239386.43117034455370.2261521182239329.12429432455217.774571168
2239303.81115304455068.910221912
#Sta/Elev= 30
       0 2214.61    18.1 2203.84    30.5 2197.76    43.9 2190.38    49.2 2186.31
    52.4 2183.16    56.7 2181.07   63.12 2180.19    69.5 2179.62    73.8 2179.61
      78 2179.79    80.2 2180.09    90.9 2181.12    98.8 2181.64   108.7 2181.77
     125 2181.51   139.2 2183.34     155 2183.91   163.5  2184.1   183.8  2184.1
   224.3 2182.88   240.5 2183.31   252.7 2184.12     269 2186.49   277.1 2188.22
   289.3 2190.37   297.4 2192.71   305.5 2195.35   309.9 2196.88   313.9 2198.56
#Mann= 3 ,-1,0
       0      .1       0   63.12    .045       0    80.2      .1       0
#XS Ineff= 2 , 0
                          176.16         2192.37
Permanent Ineff=
       F       F
Bank Sta=63.12,80.2
XS Rating Curve= 0 ,0
Exp/Cntr(USF)=0,0
Exp/Cntr=0.3,0.1

Type RM Length L Ch R = 1 ,1486    ,264,262.9,261.9
XS GIS Cut Line= 3
2239674.63634409455277.1862547062239577.68870391455099.949875854
2239568.97472007454993.362890006
#Sta/Elev= 30
       0 2222.33    13.7 2214.53    22.8  2208.9    37.2 2200.73    45.6 2196.63
    54.7 2191.77    63.8 2187.62    69.6 2185.42    75.5 2183.78   100.3 2179.63
   109.4 2177.71   114.6 2175.78   118.6 2174.25   119.7  2174.2   132.2 2175.63
   145.9 2177.39   168.7 2179.64   178.7 2179.89   186.9 2180.46   191.5 2180.32
   200.6 2179.51   217.1 2178.77   224.9 2178.68   232.9 2177.95   240.9 2178.53
   244.9 2179.09   265.4 2185.59   285.1 2192.53   298.7  2197.6     309 2200.97
#Mann= 3 ,-1,0
       0      .1       0   114.6    .045       0   132.2      .1       0
Bank Sta=114.6,132.2
XS Rating Curve= 0 ,0
Exp/Cntr(USF)=0,0
Exp/Cntr=0.3,0.1