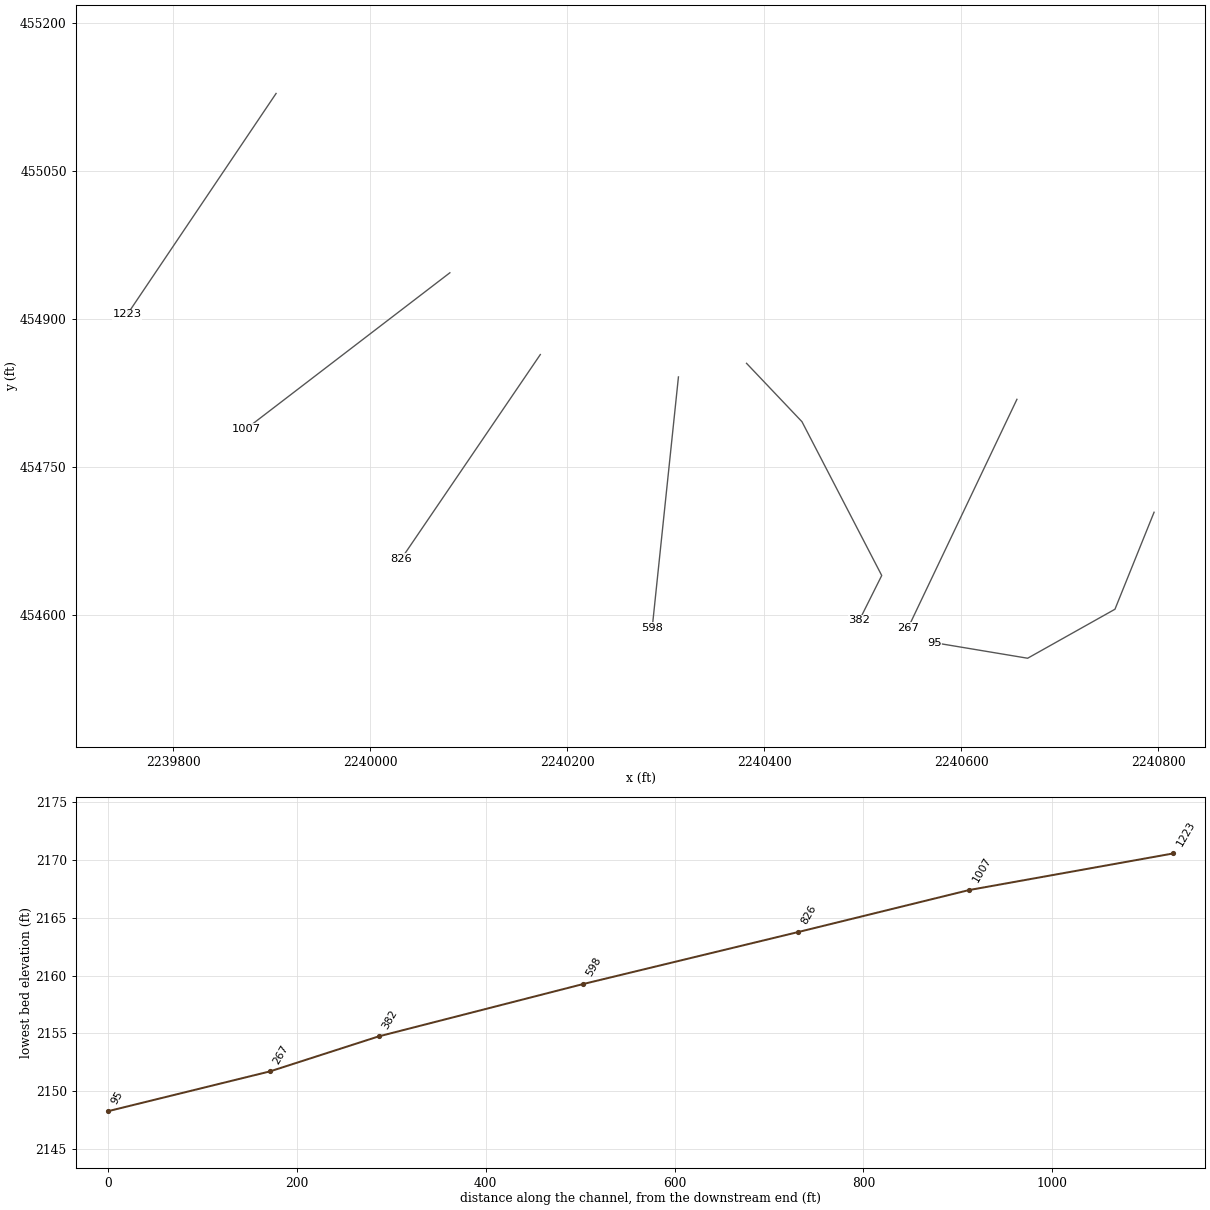
HEC-RAS study BRSHLCKRN.prj: BRSHLCKRN

--- BRSHLCKRN.g01 (geometry) --- (continued)

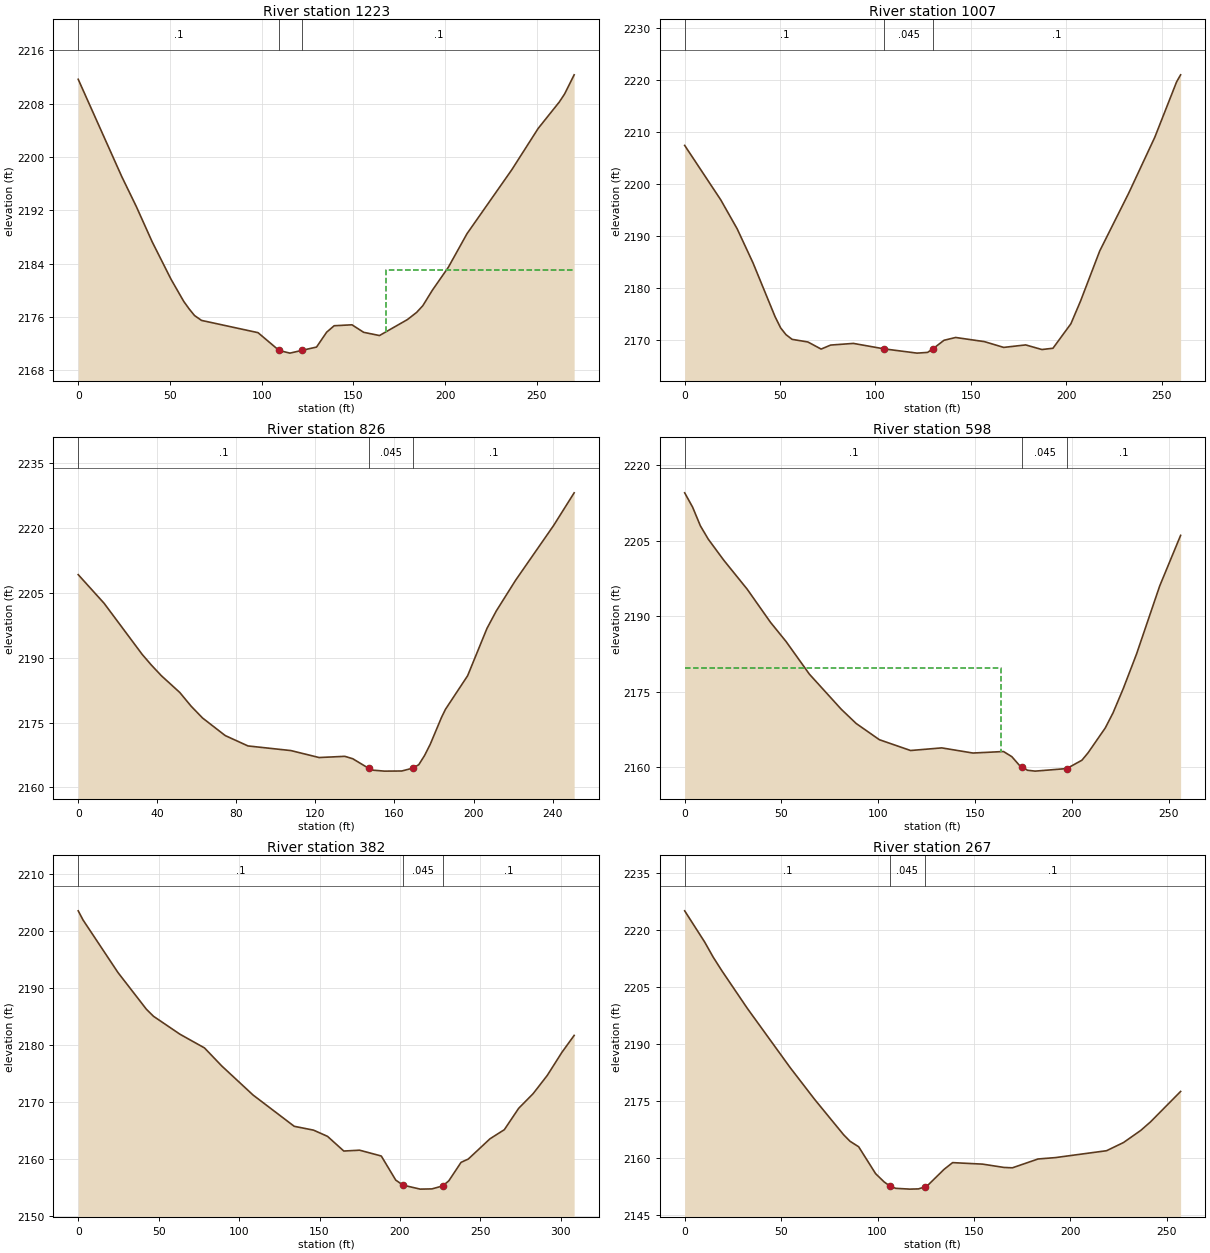
Type RM Length L Ch R = 1 ,1223    ,221,216.4,212.5
XS GIS Cut Line= 2
2239904.46334989455128.8702725062239753.36461461 454904.69110317
#Sta/Elev= 30
       0 2211.66    23.7 2197.08    31.7 2192.55    40.3 2187.28    50.6 2181.65
    57.5 2178.34    60.5 2177.19    63.4 2176.21    67.2 2175.48      98 2173.64
   109.5 2170.97   115.4 2170.57   122.2    2171   129.9 2171.48   135.4 2173.71
   139.5 2174.68   149.2 2174.82   155.6 2173.69   164.2 2173.21   179.4  2175.6
   184.4 2176.67   187.8 2177.68     193    2180   201.7 2183.44   211.9 2188.49
   236.3 2198.08   250.7 2204.29   262.2 2208.25   265.1 2209.46   270.3 2212.33
#Mann= 3 ,-1,0
       0      .1       0   109.5    .045       0   122.2      .1       0
#XS Ineff= 2 , 0
                          167.63         2183.03
Permanent Ineff=
       F       F
Bank Sta=109.5,122.2
XS Rating Curve= 0 ,0
Exp/Cntr(USF)=0,0
Exp/Cntr=0.3,0.1

Type RM Length L Ch R = 1 ,1007    ,175.8,180.9,185.8
XS GIS Cut Line= 2
2240080.91590339454946.9449979052239874.51305585454788.933248593
#Sta/Elev= 30
       0 2207.36    18.9 2196.89    27.5 2191.32    35.8 2184.77    47.4 2174.39
    50.3 2172.25    53.1 2170.95    56.3 2170.05    64.6 2169.54    71.5 2168.18
    76.5 2168.95    88.4 2169.27   104.5 2168.22   121.8  2167.4   127.3 2167.54
   130.2 2168.26   135.9 2169.87     142 2170.41   157.1 2169.61   167.2  2168.5
   178.7 2168.98   187.2 2168.09     193 2168.34   202.4 2173.05   207.5 2177.46
   217.5 2187.05   232.7 2198.18   246.4 2208.96   257.8 2219.59   259.9 2220.94
#Mann= 3 ,-1,0
       0      .1       0   104.5    .045       0   130.2      .1       0
Bank Sta=104.5,130.2
XS Rating Curve= 0 ,0
Exp/Cntr(USF)=0,0
Exp/Cntr=0.3,0.1

Type RM Length L Ch R = 1 ,826     ,219.4,227.8,235.5
XS GIS Cut Line= 2
2240172.76023268454863.9888295162240031.53723173454656.598408544
#Sta/Elev= 30
       0 2209.18    13.1 2202.56    32.4 2190.73      37 2188.29    42.1 2185.81
    51.4 2181.94    57.1 2178.79    62.9 2176.05    74.4 2171.98    85.9 2169.59
   107.6 2168.52   121.9 2166.91   134.9 2167.19   138.9 2166.63   147.1 2164.38
   149.3 2163.98     155 2163.77   163.7  2163.8   169.4 2164.48   172.3 2165.26
   175.2 2167.36   178.1 2169.98   183.8 2176.19   185.8 2178.06     197 2185.81
   206.8 2196.76   211.5 2200.78   221.3  2207.9   240.5 2220.53   250.9 2228.09
#Mann= 3 ,-1,0
       0      .1       0   147.1    .045       0   169.4      .1       0
Bank Sta=147.1,169.4
XS Rating Curve= 0 ,0
Exp/Cntr(USF)=0,0
Exp/Cntr=0.3,0.1

Type RM Length L Ch R = 1 ,598     ,204.7,216.6,224.7
XS GIS Cut Line= 2
2240312.99566019454841.274640552 2240286.3311775454586.480694787
#Sta/Elev= 30
       0 2214.48     4.1 2211.64     8.1 2207.94    12.2 2205.28    20.2 2201.11
    32.3 2195.36    44.3 2188.81    52.4 2184.97    64.4 2178.52    80.9 2171.54
    88.6 2168.72   100.6  2165.5   116.7 2163.36   132.8 2163.88   148.9 2162.86
   164.7 2163.16     169 2162.14     173 2160.39   174.4  2160.1   177.1 2159.44
   181.1 2159.27   197.4 2159.78   205.2 2161.43   208.4 2162.91   217.3 2167.85
   221.3 2170.84   226.6 2175.67   233.4 2182.47   245.4 2196.01   256.2 2206.04
#Mann= 3 ,-1,0
       0      .1       0   174.4    .045       0   197.4      .1       0
#XS Ineff= 2 , 0
          163.45 2179.66
Permanent Ineff=
       F       F
Bank Sta=174.4,197.4
XS Rating Curve= 0 ,0
Exp/Cntr(USF)=0,0
Exp/Cntr=0.3,0.1

Type RM Length L Ch R = 1 ,382     ,129.5,114.8,103.4
XS GIS Cut Line= 4
2240382.12580052454855.1006686172240438.41748621454795.846262625
2240519.39850773 454639.809660182240496.68431877454594.381282253
#Sta/Elev= 30
       0 2203.48       3 2201.88    24.7 2192.68    42.4 2186.24    46.8 2185.01
    63.3 2181.86    78.5 2179.47    89.2 2176.32   108.7 2171.22   134.3 2165.74
   146.3 2165.07     155 2163.98   165.1 2161.41   174.9 2161.56   188.4 2160.54
   197.4 2156.32   201.9 2155.44   212.6 2154.74   219.9 2154.78  226.57  2155.3
   230.4  2156.2     238 2159.43   242.5 2160.01     256 2163.56   264.9 2165.15
   273.8 2168.89   282.8 2171.46   291.6 2174.66   300.7  2178.7   308.3 2181.66
#Mann= 3 ,-1,0
       0      .1       0   201.9    .045       0  226.57      .1       0
Bank Sta=201.9,226.57
XS Rating Curve= 0 ,0
Exp/Cntr(USF)=0,0
Exp/Cntr=0.3,0.1

Type RM Length L Ch R = 1 ,267     ,181,171.8,164.3
XS GIS Cut Line= 2
2240656.67121495454818.5604515892240546.06299043454586.480694787
#Sta/Elev= 30
       0 2225.12    10.4 2216.86    14.8 2212.89    19.3  2209.3    32.5 2199.38
    54.7 2183.76    67.4 2175.37    82.4 2166.06    85.7 2164.35    90.2 2162.89
      99 2155.79   103.4 2153.62   106.4 2152.54   109.4 2151.93   116.7 2151.72
   121.2 2151.78   124.4  2152.3   125.6 2152.51   134.5 2156.95   138.9 2158.71
   154.5 2158.31   165.5 2157.44   169.9 2157.34   183.2 2159.67   192.1 2160.03
   218.7 2161.85   227.5 2164.01   236.4 2167.19   241.5 2169.46   257.1 2177.48
#Mann= 3 ,-1,0
       0      .1       0   106.4    .045       0   124.4      .1       0
Bank Sta=106.4,124.4
XS Rating Curve= 0 ,0
Exp/Cntr(USF)=0,0
Exp/Cntr=0.3,0.1

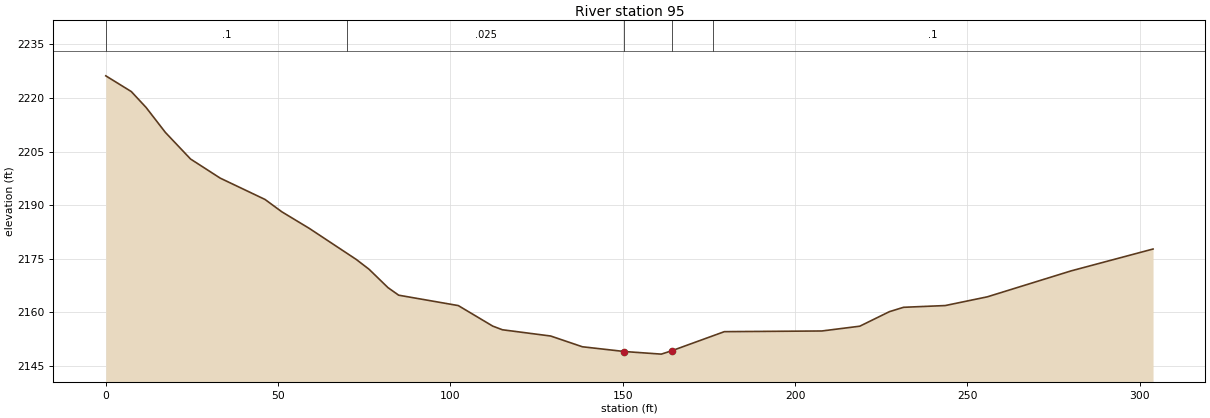
Type RM Length L Ch R = 1 ,95      ,,,
XS GIS Cut Line= 4
2240795.91906903454704.0019333382240756.19667094454605.573781162
2240667.53452271454555.8659183582240572.72747312454571.667093289
#Sta/Elev= 30
       0 2226.19     7.4 2221.79    11.7 2217.33    17.3 2210.34    24.6  2202.9
    33.2 2197.55    46.2 2191.58    51.1 2188.11    59.1 2183.45    72.7 2174.77
    76.4 2172.03    81.9 2166.88      85 2164.77   102.3 2161.86   112.3 2156.11
   115.1 2155.09   129.1 2153.34   138.3 2150.33   150.5    2149   161.2 2148.27
   164.2  2149.2   179.5 2154.56   207.8 2154.75   218.8 2156.09   227.4 2160.16
   231.5 2161.38   243.6 2161.87   255.8 2164.31   280.1 2171.57   303.9  2177.7
#Mann= 5 ,-1,0
       0      .1       0      70    .025       0   150.5    .045       0
   164.2    .025       0  176.14      .1       0
Bank Sta=150.5,164.2
XS Rating Curve= 0 ,0
Exp/Cntr(USF)=0,0
Exp/Cntr=0.3,0.1
LCMann Table=0

Chan Stop Cuts=-1
Use User Specified Reach Order=0
Composite Channel Slope=5